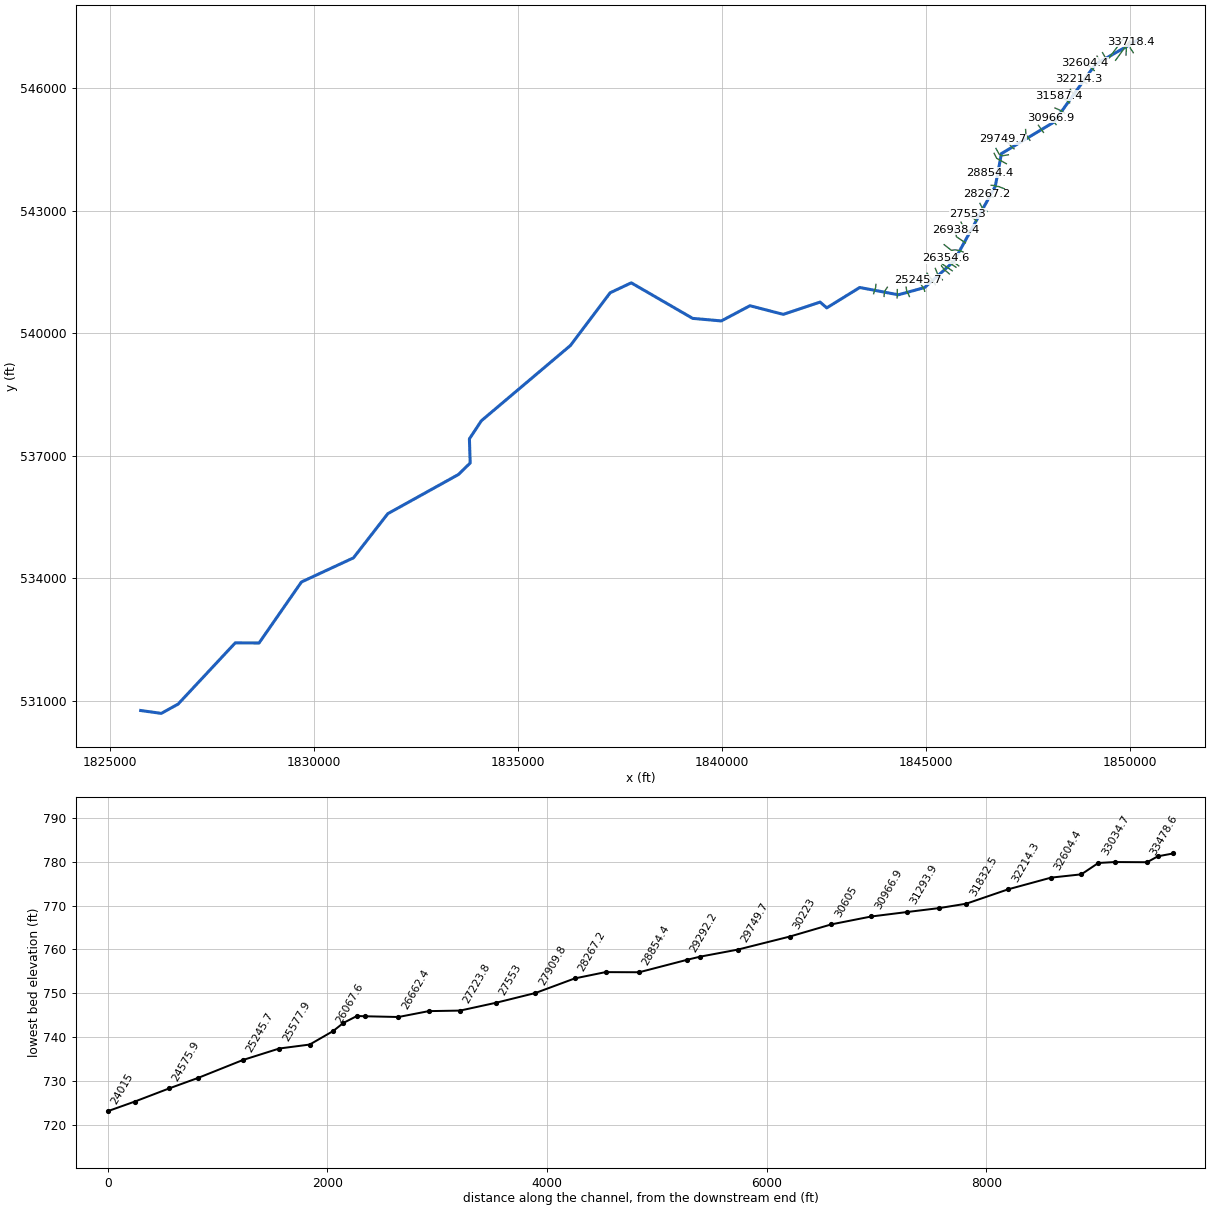
--- WILLSCK.prj (project) ---

Proj Title=WILLSCK
Current Plan=p01
Default Exp/Contr=0,0
English Units
Geom File=g01
Flow File=f01
Plan File=p01
BEGIN DESCRIPTION:
END DESCRIPTION:
DSS Export Rating Curves= 0
DSS Export Rating Curve Sorted= 0
DSS Export Volume Flow Curves= 0
DXF OffsetX= 0
DXF OffsetY= 0
DXF ScaleX= 0
DXF ScaleY= 0

--- WILLSCK.p01 (plan) ---

Plan Title=Floodplain
Program Version=4.00
Geom File=g01
Flow File=f01
K Sum by GR=0
Std Step Tol=0.01
Critical Tol=0.01
Num of Std Step Trials=20
Max Error Tol=0.3
Flow Tol Ratio=0.001
Split Flow NTrial=30
Split Flow Tol=0.02
Split Flow Ratio=0.02
Log Output Level=0
Friction Slope Method=1
Unsteady Friction Slope Method=2
Unsteady Bridges Friction Slope Method=1
Global Log Level=0
CheckData=False
Run HTab=0
Run UNet=0
Run PostProcess=0
UNET Theta=0
UNET Theta Warmup=0
UNET ZTol=0
UNET ZSATol=0
UNET MxIter=0
UNET MaxInSteps=0
UNET DtIC=0
UNET DtMin=0
UNET MaxCRTS=0
UNET WFStab=0
UNET SFStab=0
UNET WFX=0
UNET SFX=0
UNET DSS MLevel=0
UNET DZMax Abort=0
UNET Convert EG Bridges=0
UNET Use Existing IB Tables=0
UNET Froude Limit=0
UNET Froude Power=0
Write IC File=0
Echo Input=False
Echo Output=False
Write Detailed=0

--- WILLSCK.f01 (steady flow) ---

Flow Title=NFF Regression Equation
Program Version=4.10
Number of Profiles= 1
Profile Names=P100yr
River Rch & RM=WILLSCK,Main            ,33718.4
821.2942
River Rch & RM=WILLSCK,Main            ,32604.4
892.3736
River Rch & RM=WILLSCK,Main            ,31293.9
987.4906
River Rch & RM=WILLSCK,Main            ,29410.2
1075.233
River Rch & RM=WILLSCK,Main            ,28267.2
1147.436
River Rch & RM=WILLSCK,Main            ,25577.9
1249.387
River Rch & RM=WILLSCK,Main            ,21989.2
1370.341
River Rch & RM=WILLSCK,Main            ,16747.2
1701.261
River Rch & RM=WILLSCK,Main            ,13412.9
1810.714
River Rch & RM=WILLSCK,Main            ,10403.9
2000.631
River Rch & RM=WILLSCK,Main            ,6412.5
2160.166
River Rch & RM=WILLSCK,Main            ,349.6
2324.398
Boundary for River Rch & Prof#=WILLSCK,Main            , 1
Up Type= 0
Dn Type= 3
Dn Slope=0.003
DSS Import GetInterval= 0
DSS Import GetPeak= 0
DSS Import FillOption= 0

--- WILLSCK.g01 (geometry) ---

Geom Title=USGS 10m DEM
Program Version=4.10

River Reach=WILLSCK         ,Main
Reach XY= 30
     1850257.468       547220.86     1849153.491      546592.031
     1848136.564      545174.063     1846852.028      544403.549
     1846700.757      543602.646     1845682.137      541758.698
     1844969.433      541121.214     1844325.366      540943.594
     1843378.721      541122.299     1842571.429      540623.167
     1842407.584      540764.226     1841505.891      540463.662
     1840688.647      540675.365     1839986.825      540302.969
     1839285.001      540365.469     1837779.793      541236.563
      1837263.27      540993.176     1836287.792      539699.773
     1834106.616      537856.354     1833813.647      537412.344
     1833832.931      536821.084     1833545.418      536539.948
     1831813.647      535579.011     1830972.501      534496.979
     1829697.762      533905.833     1828658.452       532410.06
     1828075.366      532413.646     1826674.325      530912.344
     1826262.866      530685.781     1825757.542      530756.173

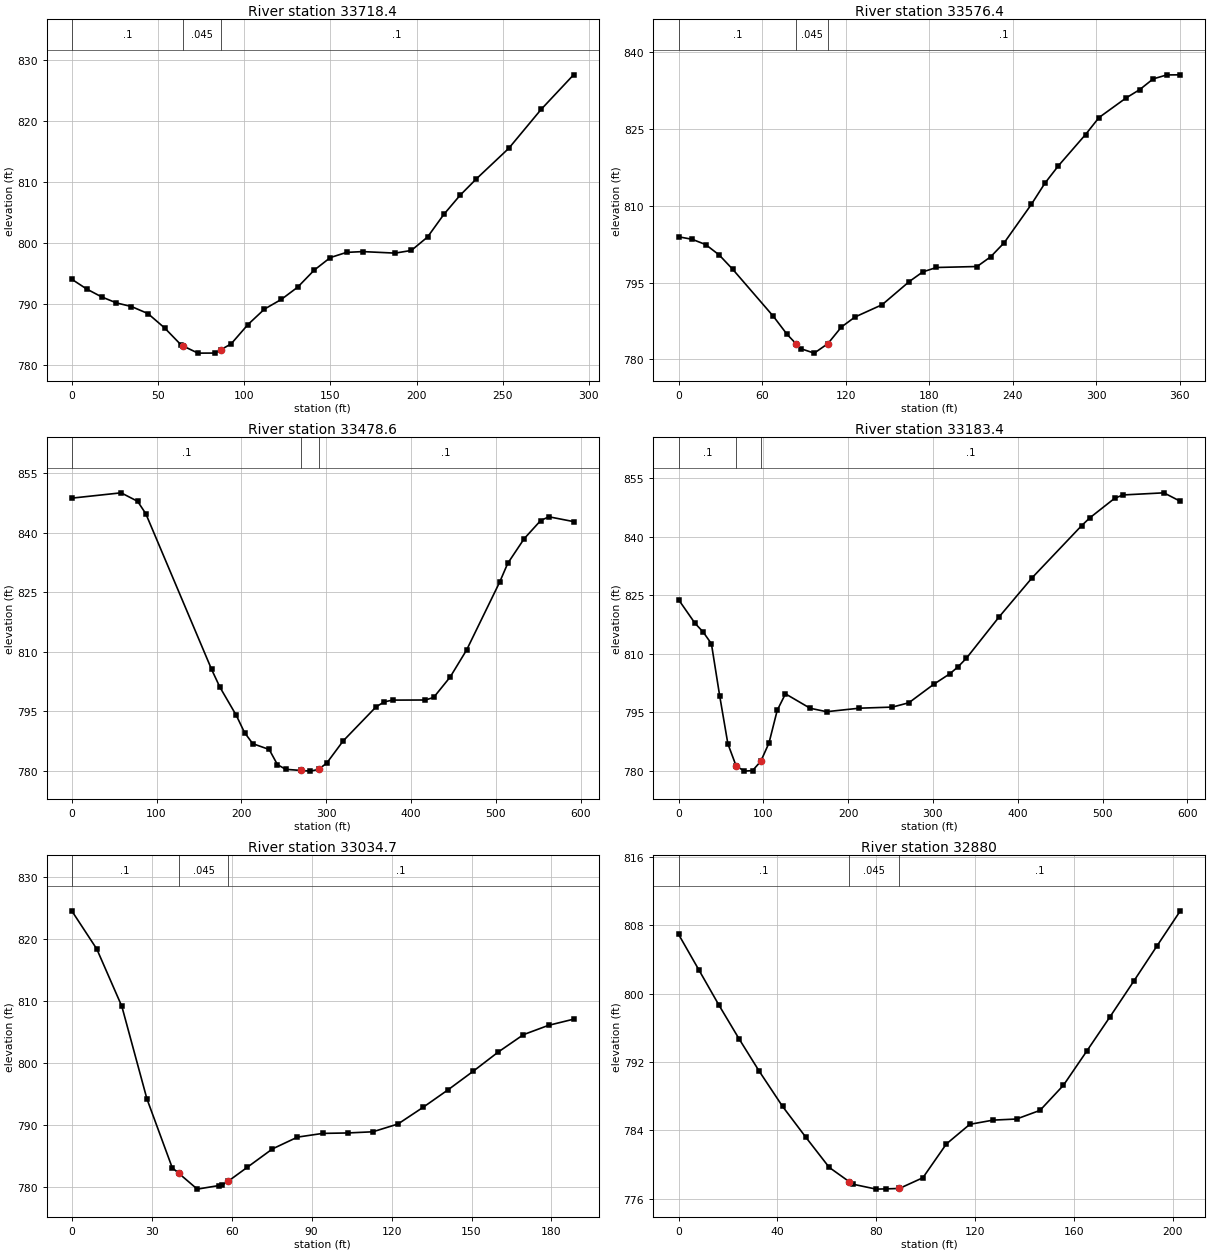
Type RM Length L Ch R = 1 ,33718.4 ,157.1,142,127.1
XS GIS Cut Line= 4
     1850081.447      546875.483     1850064.954      546905.865
     1850009.398      546984.858     1850018.079       547144.58
#Sta/Elev= 30
       0     794     8.6  792.41    17.3  791.11    25.9  790.12    34.6  789.53
    44.2  788.37    53.9  786.01    63.5  783.21    64.5  783.07    73.2  781.89
    82.9   781.9   86.36  782.42    92.5  783.42   102.2  786.57   111.8  789.11
   121.5  790.68   131.1  792.71   140.6  795.48     150  797.55   159.4   798.4
   168.8  798.53   187.6  798.28     197  798.72   206.4  800.92   215.8  804.61
   225.2  807.74   234.6  810.42   253.5  815.45   272.3  821.84   291.1   827.5
#Mann= 3 , 0 , 0
       0      .1       0    64.5    .045       0   86.36      .1       0
Bank Sta=64.5,86.36
XS Rating Curve= 0 ,0
Exp/Cntr=0.3,0.1

Type RM Length L Ch R = 1 ,33576.4 ,118.8,97.8,83
XS GIS Cut Line= 3
     1849904.466       546818.01     1849916.185      547041.968
      1850000.82      547148.739
#Sta/Elev= 30
       0  803.93     9.8  803.44    19.5  802.41    29.2  800.39      39  797.57
    68.2  788.39      78  784.89    84.7  782.98    87.8   782.1    97.5  781.23
   107.3  783.08     117  786.32   126.8  788.28   146.3  790.68   165.8   795.2
   175.5  797.08   185.3  797.94   214.5  798.13   224.3  800.04     234  802.78
   253.5  810.26   263.2  814.38   272.9  817.78   292.4  823.88   302.1   827.2
   321.6  831.03   331.3  832.64     341  834.74   350.8  835.51   360.5  835.53
#Mann= 3 , 0 , 0
       0      .1       0    84.7    .045       0   107.3      .1       0
Bank Sta=84.7,107.3
XS Rating Curve= 0 ,0
Exp/Cntr=0.3,0.1

Type RM Length L Ch R = 1 ,33478.6 ,298.6,295.2,283.3
XS GIS Cut Line= 2
     1849647.956      546690.405     1849996.914       547168.27
#Sta/Elev= 30
       0  848.69    58.2  850.03    77.6   847.9    87.3  844.77   164.9  805.52
   174.6  801.07     194  793.94   203.7  789.61   213.4   786.8   232.8  785.34
   242.5  781.53   252.2  780.34   270.2  780.05   281.3  779.88     291  780.31
   300.7  781.92   320.1  787.51   358.9   796.1   368.6  797.34   378.3  797.78
   417.1  797.81   426.8  798.47   446.2   803.6   465.6  810.42   504.4  827.45
   514.1  832.26   533.5  838.48   552.9  843.04   562.6  843.99   591.7  842.78
#Mann= 3 , 0 , 0
       0      .1       0   270.2    .045       0     291      .1       0
Bank Sta=270.2,291
XS Rating Curve= 0 ,0
Exp/Cntr=0.3,0.1

Type RM Length L Ch R = 1 ,33183.4 ,111.5,148.7,188.1
XS GIS Cut Line= 2
      1849494.31      546750.301     1849843.268      547228.166
#Sta/Elev= 30
       0  823.91    19.4  817.84    29.1  815.58    38.8  812.58    48.5  799.28
    58.2  786.93    67.9  781.27    77.6  779.92    87.3  780.06      97  782.44
   106.7  787.15   116.4  795.52   126.1  799.74   155.2  796.04   174.6  795.16
   213.4  796.06   252.2  796.34   271.6  797.45   300.7  802.15   320.1  804.91
   329.8  806.71   339.5  808.88   378.3  819.54   417.1  829.54   475.3  842.86
     485  844.87   514.1  849.85   523.8  850.73   572.3  851.28   591.7  849.11
#Mann= 3 , 0 , 0
       0      .1       0    67.9    .045       0      97      .1       0
Bank Sta=67.9,97
XS Rating Curve= 0 ,0
Exp/Cntr=0.3,0.1

Type RM Length L Ch R = 1 ,33034.7 ,153.2,154.7,156
XS GIS Cut Line= 2
     1849421.393      546713.843     1849328.945      546877.905
#Sta/Elev= 24
       0  824.55     9.4  818.39    18.8  809.15    28.2  794.26    37.7  783.16
    40.1  782.28    47.1  779.71    55.1  780.28    56.5  780.38   58.81  781.02
    65.9  783.24    75.3  786.19    84.7  788.09    94.2  788.69   103.6  788.76
     113  788.95   122.4   790.2   131.8  792.88   141.2  795.71   150.6  798.69
   160.1  801.82   169.5   804.6   178.9   806.1   188.3  807.09
#Mann= 3 , 0 , 0
       0      .1       0    40.1    .045       0   58.81      .1       0
Bank Sta=40.1,58.81
XS Rating Curve= 0 ,0
Exp/Cntr=0.3,0.1

Type RM Length L Ch R = 1 ,32880   ,268.8,275.6,282.5
XS GIS Cut Line= 3
     1849314.622      546633.114     1849285.977      546648.739
     1849193.529      546791.968
#Sta/Elev= 25
       0  806.93     8.2  802.78    16.3  798.67    24.5   794.7    32.6  790.94
    42.1   786.8    51.6  783.16      61  779.66    69.1  777.99    70.5   777.7
      80  777.12    84.1  777.15    89.4   777.2    98.9  778.45   108.4   782.4
   117.9   784.7   127.3  785.19   136.8  785.32   146.3  786.33   155.8  789.27
   165.2  793.25   174.7   797.3   184.2  801.42   193.6  805.54   203.1  809.67
#Mann= 3 , 0 , 0
       0      .1       0    69.1    .045       0    89.4      .1       0
Bank Sta=69.1,89.4
XS Rating Curve= 0 ,0
Exp/Cntr=0.3,0.1

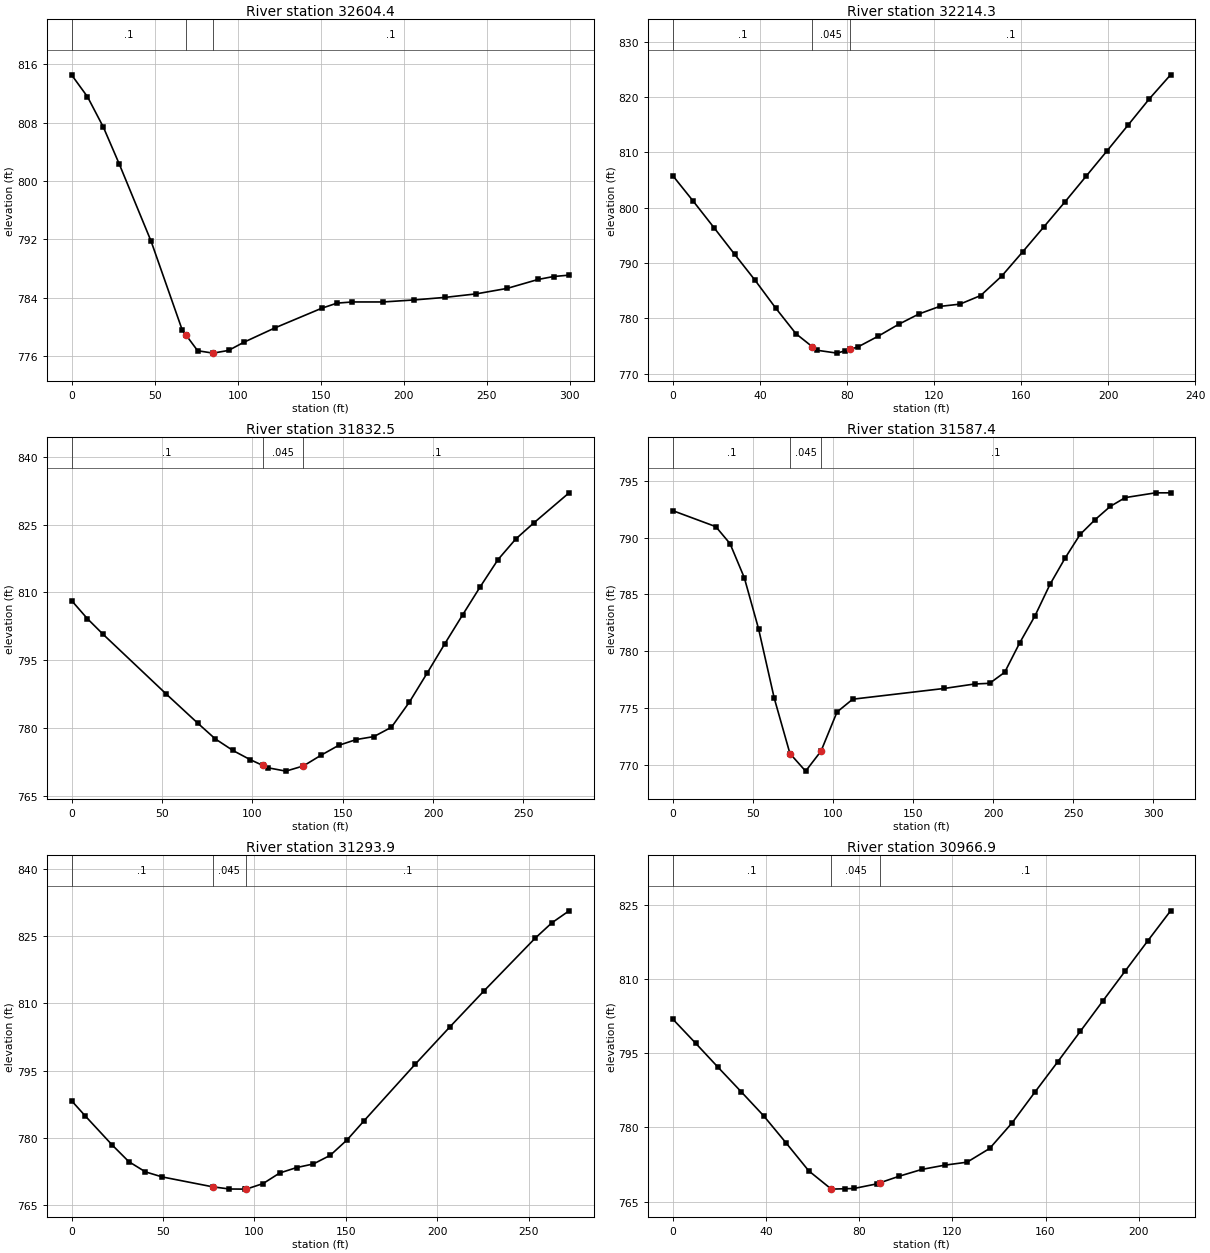
Type RM Length L Ch R = 1 ,32604.4 ,386.5,390,393.5
XS GIS Cut Line= 4
     1849123.216      546439.103     1849090.664       546474.26
     1849004.727      546545.874     1848896.654      546634.416
#Sta/Elev= 23
       0  814.55     9.6  811.54    19.2  807.35    28.8  802.27    47.9  791.71
    66.6  779.56    68.8  778.88    75.9   776.7    85.2  776.37    94.5  776.74
   103.8  777.87   122.5  779.84   150.5  782.52   159.8  783.23   169.1  783.39
   187.7  783.39   206.4  783.67     225  784.02   243.6   784.5   262.2  785.25
   280.9  786.48   290.2  786.88   299.5  787.07
#Mann= 3 , 0 , 0
       0      .1       0    68.8    .045       0    85.2      .1       0
Bank Sta=68.8,85.2
XS Rating Curve= 0 ,0
Exp/Cntr=0.3,0.1

Type RM Length L Ch R = 1 ,32214.3 ,382.4,381.8,380.9
XS GIS Cut Line= 3
     1848942.227      546120.093     1848821.133       546193.01
     1848743.008      546232.072
#Sta/Elev= 28
       0  805.74     9.4  801.13    18.8  796.41    28.3  791.59    37.7  786.89
    47.1   781.9    56.5  777.22    64.1  774.84      66  774.24    75.4  773.71
    79.1  774.14   81.49  774.44    84.8  774.79    94.2  776.75   103.7  778.92
   113.1   780.8   122.5  782.15   131.9  782.57   141.4  784.12   151.1  787.65
   160.8  792.06   170.5  796.56   180.2  801.08   189.9  805.71   199.6  810.33
   209.3  815.01     219  819.72   228.7  824.03
#Mann= 3 , 0 , 0
       0      .1       0    64.1    .045       0   81.49      .1       0
Bank Sta=64.1,81.49
XS Rating Curve= 0 ,0
Exp/Cntr=0.3,0.1

Type RM Length L Ch R = 1 ,31832.5 ,246.2,245.2,244.3
XS GIS Cut Line= 4
      1848750.82       545824.52      1848681.81      545834.937
     1848591.966       545893.53     1848539.883      545976.864
#Sta/Elev= 26
       0  808.21     8.7  804.22    17.4  800.75    52.3  787.54    69.8  781.06
    79.5  777.58    89.3     775      99  772.94   105.8   771.7   108.8  771.16
   118.6  770.43   128.3  771.58     138  773.94   147.8  776.14   157.6  777.43
   167.3  778.08     177  780.15   186.9   785.7   196.7   792.1   206.5  798.62
   216.4  805.04   226.2   811.3     236  817.29   245.8  821.84   255.7  825.37
   275.3  832.06
#Mann= 3 , 0 , 0
       0      .1       0   105.8    .045       0   128.3      .1       0
Bank Sta=105.8,128.3
XS Rating Curve= 0 ,0
Exp/Cntr=0.3,0.1

Type RM Length L Ch R = 1 ,31587.4 ,291.9,293.4,295
XS GIS Cut Line= 4
     1848522.956      545646.135     1848485.195      545683.895
     1848421.393      545729.468      1848269.05      545823.218
#Sta/Elev= 25
       0  792.38    26.7  790.98    35.6  789.48    44.5  786.48    53.4  781.98
    63.2  775.86      73  770.98    82.8  769.43    92.4  771.19   102.4  774.64
   112.2  775.77   169.5  776.72   188.3  777.11   197.7  777.17   207.1  778.14
   216.5  780.74     226  783.11   235.4  785.89   244.8   788.2   254.2  790.29
   263.6   791.6     273  792.76   282.4  793.54   301.3  793.96   310.7  793.96
#Mann= 3 , 0 , 0
       0      .1       0      73    .045       0    92.4      .1       0
Bank Sta=73,92.4
XS Rating Curve= 0 ,0
Exp/Cntr=0.3,0.1

Type RM Length L Ch R = 1 ,31293.9 ,334.6,327,319.4
XS GIS Cut Line= 4
      1848400.56      545390.926     1848384.935      545406.551
     1848283.372      545469.051     1848163.581      545521.135
#Sta/Elev= 23
       0  788.27     7.4  784.91    22.1  778.43    31.3  774.67    40.4  772.38
    49.6  771.25    77.1  769.05    86.3  768.56    94.8  768.53    95.5  768.53
   104.7  769.77   113.8  772.13     123  773.34   132.2  774.15   141.4  776.07
   150.7  779.55     160  783.83     188  796.47   206.7  804.69   225.3  812.71
   253.3  824.49   262.6  827.99     272  830.66
#Mann= 3 , 0 , 0
       0      .1       0    77.1    .045       0    95.5      .1       0
Bank Sta=77.1,95.5
XS Rating Curve= 0 ,0
Exp/Cntr=0.3,0.1

Type RM Length L Ch R = 1 ,30966.9 ,363.3,361.9,360.2
XS GIS Cut Line= 2
     1848190.925      545114.885     1848055.508      545280.249
#Sta/Elev= 25
       0  801.84     9.7  797.02    19.4  792.12    29.2  787.24    38.9  782.35
    48.6  776.83    58.3   771.2      68  767.51    73.9  767.59    77.7  767.64
    87.4  768.56    88.9   768.8    97.2  770.13   106.9   771.5   116.6  772.35
   126.3  772.96     136  775.74   145.7  780.95   155.4  787.11   165.2  793.24
   174.9   799.4   184.6  805.56   194.3  811.68     204  817.78   213.7  823.79
#Mann= 3 , 0 , 0
       0      .1       0      68    .045       0    88.9      .1       0
Bank Sta=68,88.9
XS Rating Curve= 0 ,0
Exp/Cntr=0.3,0.1

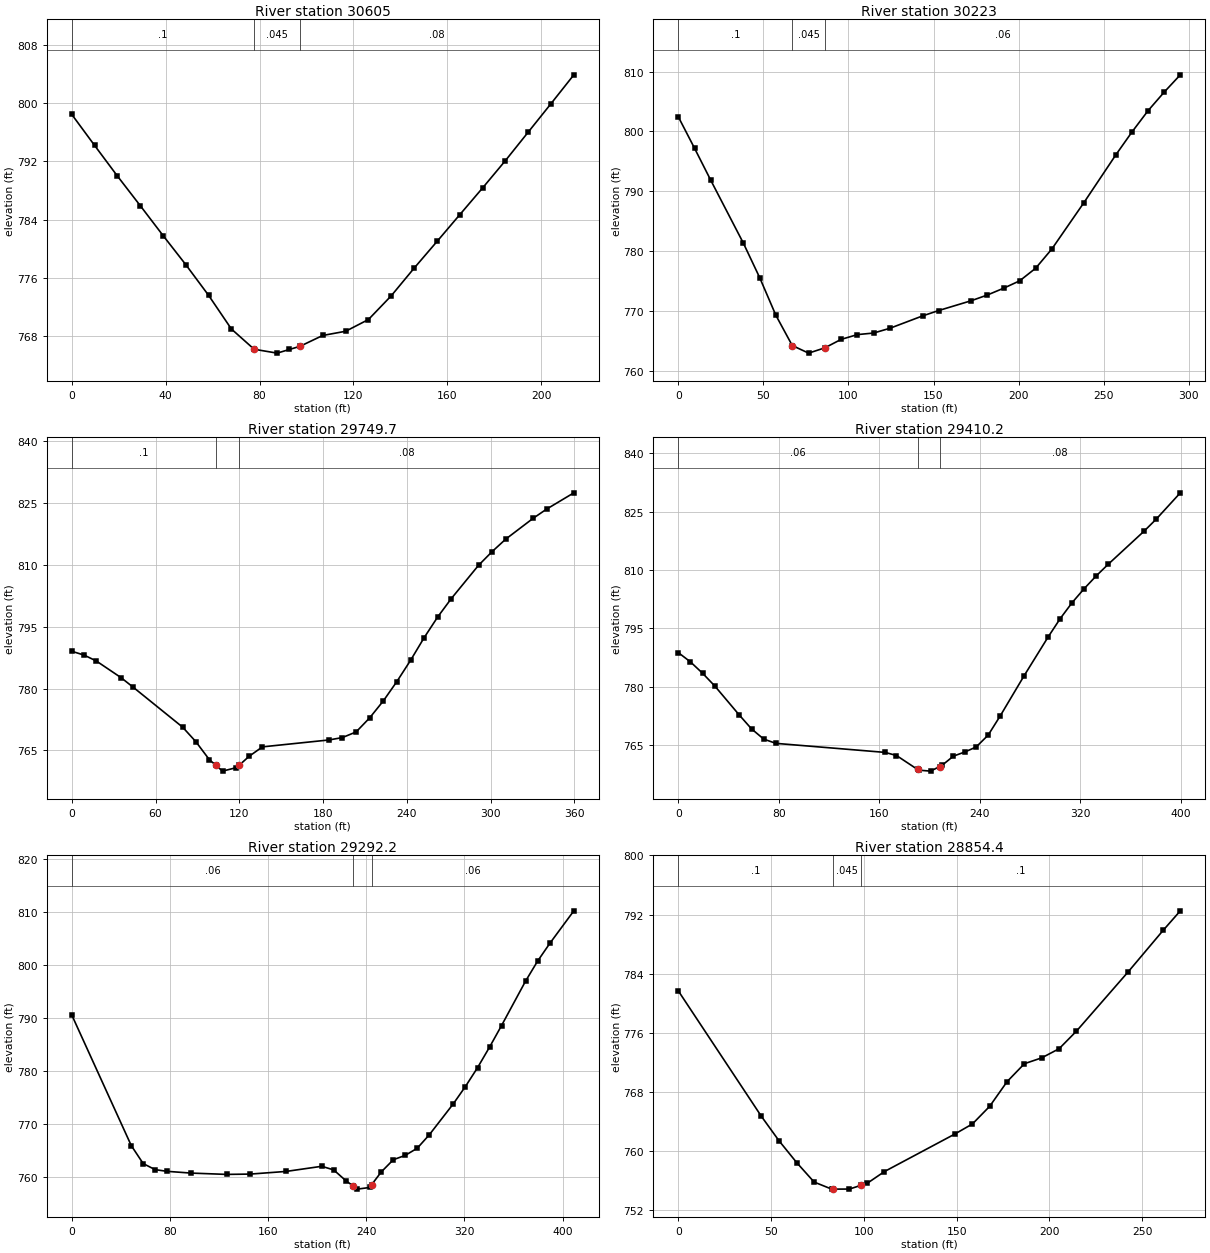
Type RM Length L Ch R = 1 ,30605   ,382.5,382.1,381.9
XS GIS Cut Line= 2
     1847881.029      544923.478     1847757.331      545097.958
#Sta/Elev= 24
       0  798.45     9.7  794.21    19.4  790.02    29.2  785.93    38.9  781.84
    48.6  777.84    58.3  773.64      68  769.03    77.7  766.25    87.5  765.72
    92.7  766.22    97.2  766.65   106.9  768.14   116.7  768.72   126.4  770.33
   136.1  773.58   145.8  777.35   155.6  781.03   165.3   784.7     175  788.36
   184.7   792.1   194.4     796   204.2  799.94   213.9  803.88
#Mann= 3 , 0 , 0
       0      .1       0    77.7    .045       0    97.2     .08       0
Bank Sta=77.7,97.2
XS Rating Curve= 0 ,0
Exp/Cntr=0.3,0.1

Type RM Length L Ch R = 1 ,30223   ,470.7,473.3,475.5
XS GIS Cut Line= 3
       1847550.3      544729.468     1847452.643      544871.395
     1847443.529      544993.791
#Sta/Elev= 27
       0  802.47     9.6  797.18    19.1  791.84    38.3   781.3    47.9  775.52
    57.4  769.23      67  764.19    76.6  762.92    86.1   763.8    95.7  765.22
   105.3  766.02   114.8  766.28   124.4  767.08   143.6  769.15   153.1  770.05
   172.3   771.7   181.7  772.65   191.2  773.78   200.6  775.01     210  777.12
   219.5  780.33   238.4  788.11   257.2  796.12   266.7  799.95   276.1  803.49
   285.6   806.6     295  809.47
#Mann= 3 , 0 , 0
       0      .1       0      67    .045       0    86.1     .06       0
Bank Sta=67,86.1
XS Rating Curve= 0 ,0
Exp/Cntr=0.3,0.1

Type RM Length L Ch R = 1 ,29749.7 ,331,339.4,347.5
XS GIS Cut Line= 4
     1847159.675      544521.135     1847099.779      544573.218
      1847025.56      544660.458     1846886.237      544750.301
#Sta/Elev= 30
       0  789.04     8.8  788.12    17.6  786.68    35.3  782.64    44.1  780.29
    79.4  770.63    88.9   767.1    98.5  762.76   103.2  761.37     108  759.95
   117.6  760.77  120.11  761.43   127.1  763.56   136.6  765.84   184.4  767.52
   193.9   768.1   203.7  769.46   213.4  772.87   223.2  776.99   232.9  781.69
   242.7  786.83   252.4  792.32   262.2  797.39   271.9  801.83   291.4   809.9
   301.2  813.25   310.9  816.26   330.4  821.28   340.2  823.55   359.7   827.5
#Mann= 3 , 0 , 0
       0      .1       0   103.2    .045       0  120.11     .08       0
Bank Sta=103.2,120.11
XS Rating Curve= 0 ,0
Exp/Cntr=0.3,0.1

Type RM Length L Ch R = 1 ,29410.2 ,118.4,118.1,117.9
XS GIS Cut Line= 4
     1847021.654      544373.999     1846868.008       544349.26
     1846796.393      544388.322     1846716.966      544530.249
#Sta/Elev= 30
       0  788.81     9.7  786.42    19.4  783.49    29.2  780.19    48.6  772.77
    58.4   769.2    68.1  766.58    77.8  765.49   164.7  763.17   173.8  762.37
  190.61  758.78   191.9   758.6   200.9  758.36   208.1  759.52     210  759.83
   219.1  762.21   228.1  763.26   237.2  764.55   246.8  767.61   256.3  772.49
   275.5   782.9   294.6  792.84   304.2  797.55   313.7  801.65   323.3  805.24
   332.9  808.52   342.4  811.49   371.1  820.03   380.7   823.1   399.8  829.83
#Mann= 3 , 0 , 0
       0     .06       0  190.61    .045       0   208.1     .08       0
Bank Sta=190.61,208.1
XS Rating Curve= 0 ,0
Exp/Cntr=0.3,0.1

Type RM Length L Ch R = 1 ,29292.2 ,433.1,437.8,442.3
XS GIS Cut Line= 3
     1846972.175      544155.249     1846735.195      544288.062
     1846672.695      544410.458
#Sta/Elev= 30
       0  790.52    48.5  765.86    58.2  762.47    67.9  761.33    77.6  761.01
      97  760.68   126.1  760.43   145.5  760.49   174.6  760.99   203.7  761.96
   213.4  761.28   223.2  759.27   229.4  758.22   232.8  757.65   242.6  757.96
   244.4  758.51   252.2   760.9     262   763.2   271.7  764.02   281.5  765.37
   291.3   767.9   310.9  773.76   320.7     777   330.6  780.56   340.4  784.45
   350.2  788.53   369.8  796.93   379.6   800.7   389.5  804.03   409.1  810.18
#Mann= 3 , 0 , 0
       0     .06       0   229.4    .045       0   244.4     .06       0
Bank Sta=229.4,244.4
XS Rating Curve= 0 ,0
Exp/Cntr=0.3,0.1

Type RM Length L Ch R = 1 ,28854.4 ,307.1,306.6,305.9
XS GIS Cut Line= 4
     1846836.758       543880.51     1846796.393      543900.041
      1846688.32      543935.197     1846576.341      543931.291
#Sta/Elev= 22
       0  781.67    44.8  764.66    54.3  761.35    63.8   758.4    73.2  755.76
    82.7   754.8    83.3   754.8    92.2  754.81    98.3   755.3   101.7  755.57
   111.1  757.18     149  762.26   158.5  763.63   167.8  766.02   177.2  769.37
   186.5  771.79   195.8  772.58   205.2  773.82   214.5  776.19   242.5  784.26
   261.2  789.84   270.5   792.5
#Mann= 3 , 0 , 0
       0      .1       0    83.3    .045       0    98.3      .1       0
Bank Sta=83.3,98.3
XS Rating Curve= 0 ,0
Exp/Cntr=0.3,0.1

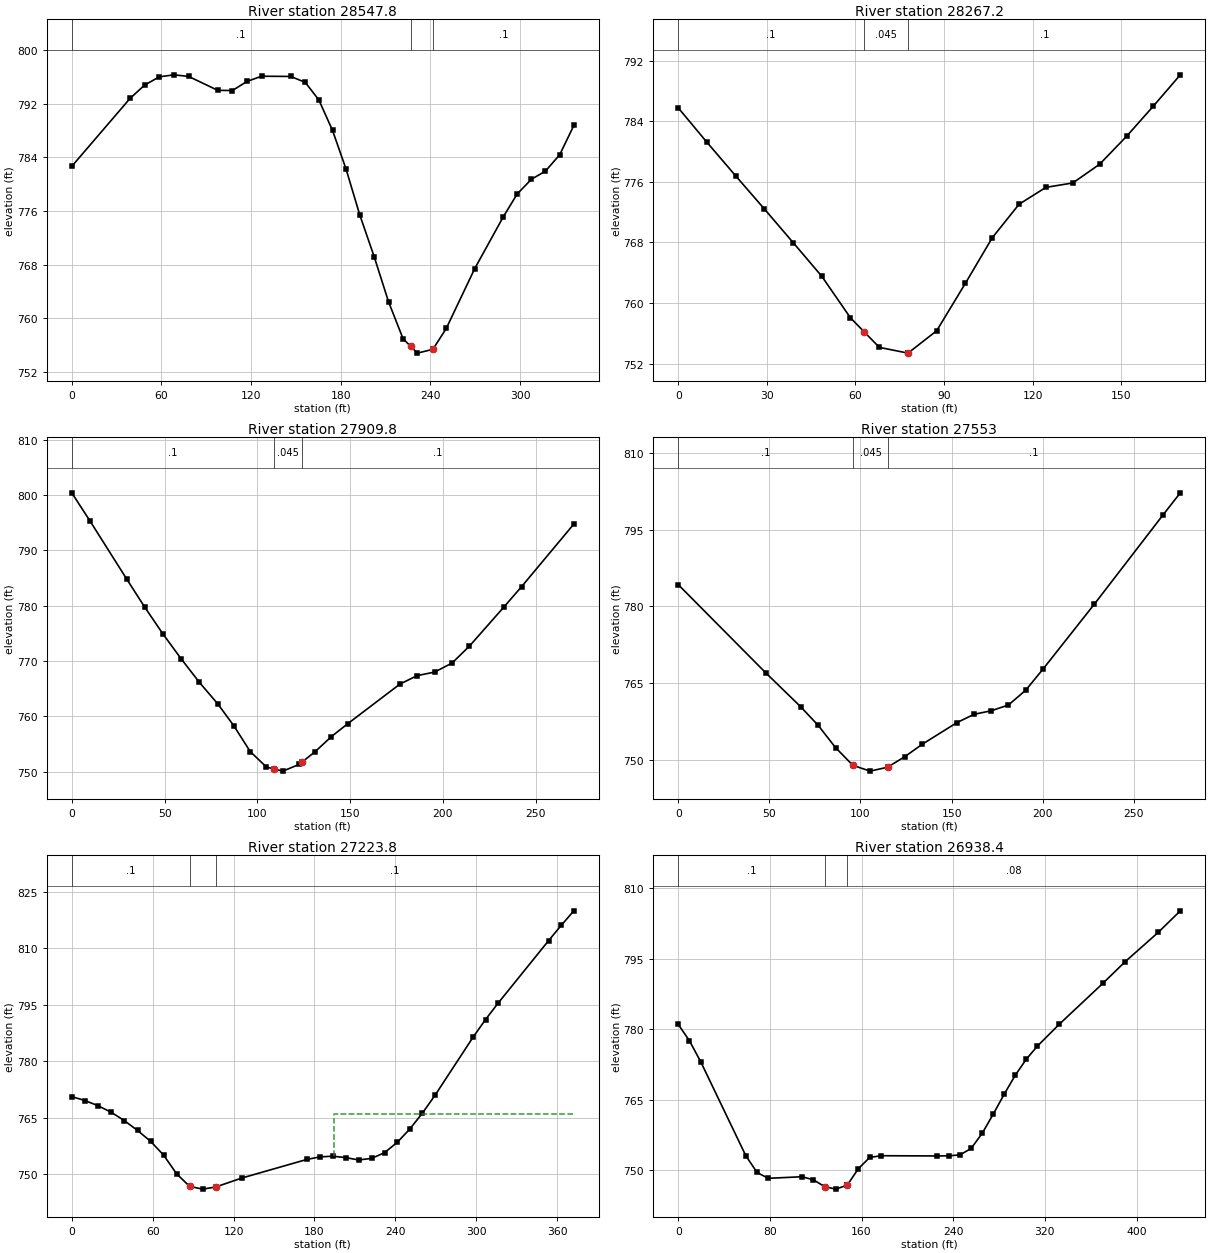
Type RM Length L Ch R = 1 ,28547.8 ,281.1,280.6,280.1
XS GIS Cut Line= 5
     1846922.695      543541.968     1846776.826      543598.121
     1846740.404       543599.26     1846676.602      543621.395
     1846601.081      543626.603
#Sta/Elev= 30
       0  782.65    39.1  792.79    48.8  794.76    58.6  795.98    68.4  796.28
    78.2  796.04    97.7  793.97   107.5  793.94   117.2  795.29     127  796.07
   146.5  796.04   156.3  795.15   165.4  792.52   174.5     788   183.6  782.21
   192.7  775.44   202.4  769.18     212  762.47   221.7  756.98   226.7  755.86
   231.3  754.83   241.7   755.4   250.6   758.5   269.7  767.43   288.7   775.1
   298.1  778.54   307.6  780.72     317  781.94   326.5  784.36     336  788.74
#Mann= 3 , 0 , 0
       0      .1       0   226.7    .045       0   241.7      .1       0
Bank Sta=226.7,241.7
XS Rating Curve= 0 ,0
Exp/Cntr=0.3,0.1

Type RM Length L Ch R = 1 ,28267.2 ,367.5,357.3,346.9
XS GIS Cut Line= 3
     1846649.258      543334.937     1846558.112      543368.791
     1846493.008      543401.343
#Sta/Elev= 21
       0  785.78     9.7  781.24    19.4  776.82    29.2  772.41    38.9  767.99
    48.6  763.54    58.3  758.06    62.9  756.22    68.1  754.15    77.8  753.39
    77.9  753.42    87.5  756.34    97.2  762.59   106.3  768.61   115.4  773.05
   124.5  775.28   133.6  775.86   142.7  778.34   151.8  782.02   160.9  786.02
     170  790.14
#Mann= 3 , 0 , 0
       0      .1       0    62.9    .045       0    77.9      .1       0
Bank Sta=62.9,77.9
XS Rating Curve= 0 ,0
Exp/Cntr=0.3,0.1

Type RM Length L Ch R = 1 ,27909.8 ,350.2,356.8,363.2
XS GIS Cut Line= 4
     1846499.518      542988.583     1846430.508      543026.343
     1846382.331      543077.124     1846323.737      543183.895
#Sta/Elev= 26
       0  800.42     9.8  795.34    29.5  784.87    39.3  779.74    49.2  774.85
      59  770.36    68.8  766.11    78.7  762.22    87.4  758.23    96.2  753.59
   104.9   750.8   108.8  750.48   113.7  750.07   122.4  751.27   123.8  751.64
   131.2  753.62   139.9  756.32   148.7  758.65   176.8  765.82   186.1  767.35
   195.5  767.99   204.9  769.63   214.2  772.67     233  779.83   242.4  783.47
   270.5  794.77
#Mann= 3 , 0 , 0
       0      .1       0   108.8    .045       0   123.8      .1       0
Bank Sta=108.8,123.8
XS Rating Curve= 0 ,0
Exp/Cntr=0.3,0.1

Type RM Length L Ch R = 1 ,27553   ,331.4,329.2,326.9
XS GIS Cut Line= 4
     1846236.497      542752.905     1846189.622      542801.083
     1846115.404      542844.051     1846030.768      542932.593
#Sta/Elev= 20
       0  784.27      48  767.06    67.2  760.42    76.8  756.79    86.3  752.46
    95.8     749    96.1  748.96   105.3  747.86   114.9  748.63   124.4   750.7
   133.9  753.11     153  757.35   162.4  758.96   171.8  759.65   181.2  760.77
   190.7  763.67   200.1  767.75   228.4  780.49     266  797.87   275.5  802.19
#Mann= 3 , 0 , 0
       0      .1       0    96.1    .045       0   114.9      .1       0
Bank Sta=96.1,114.9
XS Rating Curve= 0 ,0
Exp/Cntr=0.3,0.1

Type RM Length L Ch R = 1 ,27223.8 ,284.7,285.4,286.1
XS GIS Cut Line= 4
      1846081.55      542440.405     1846060.716      542495.093
     1845920.091      542596.655     1845861.497       542724.26
#Sta/Elev= 30
       0   770.6     9.8  769.56    19.5  768.18    29.3  766.44      39  764.23
    48.8  761.62    58.5  758.73    68.2  755.05    77.8  750.11    87.4  746.79
    97.1  746.06   106.7  746.62     126  748.99   174.2  753.92   183.8   754.6
   193.4   754.8   203.1  754.43   212.7   753.8   222.4  754.21     232  755.74
   241.4  758.46   250.7     762   260.1  766.23   269.4  770.94   297.5  786.29
   306.9  791.05   316.2  795.39   353.7     812     363  816.02   372.4  819.89
#Mann= 3 , 0 , 0
       0      .1       0    87.4    .045       0   106.7      .1       0
#XS Ineff= 2 , 0
                          194.15          765.92
Permanent Ineff=
       F       F
Bank Sta=87.4,106.7
XS Rating Curve= 0 ,0
Exp/Cntr=0.3,0.1

Type RM Length L Ch R = 1 ,26938.4 ,266.1,276,285.4
XS GIS Cut Line= 3
     1845968.268      542217.749     1845748.216      542366.187
     1845720.872       542536.76
#Sta/Elev= 30
       0     781     9.8  777.51    19.7  773.01      59  753.04    68.8  749.48
    78.6  748.24   108.1  748.58     118  747.92   127.8  746.47   137.6  745.94
   147.1  746.76   147.5  746.79   157.3  750.32   167.1  752.68     177  753.05
   226.1     753   235.9  753.03   245.8  753.22   255.6  754.59   265.4  757.86
     275  761.93   284.6  766.19   294.2   770.2   303.8   773.6   313.4  776.36
   332.6  781.04     371  789.83   390.2  794.37     419   800.6   438.2  805.17
#Mann= 3 , 0 , 0
       0      .1       0   127.8    .045       0   147.1     .08       0
Bank Sta=127.8,147.1
XS Rating Curve= 0 ,0
Exp/Cntr=0.3,0.1

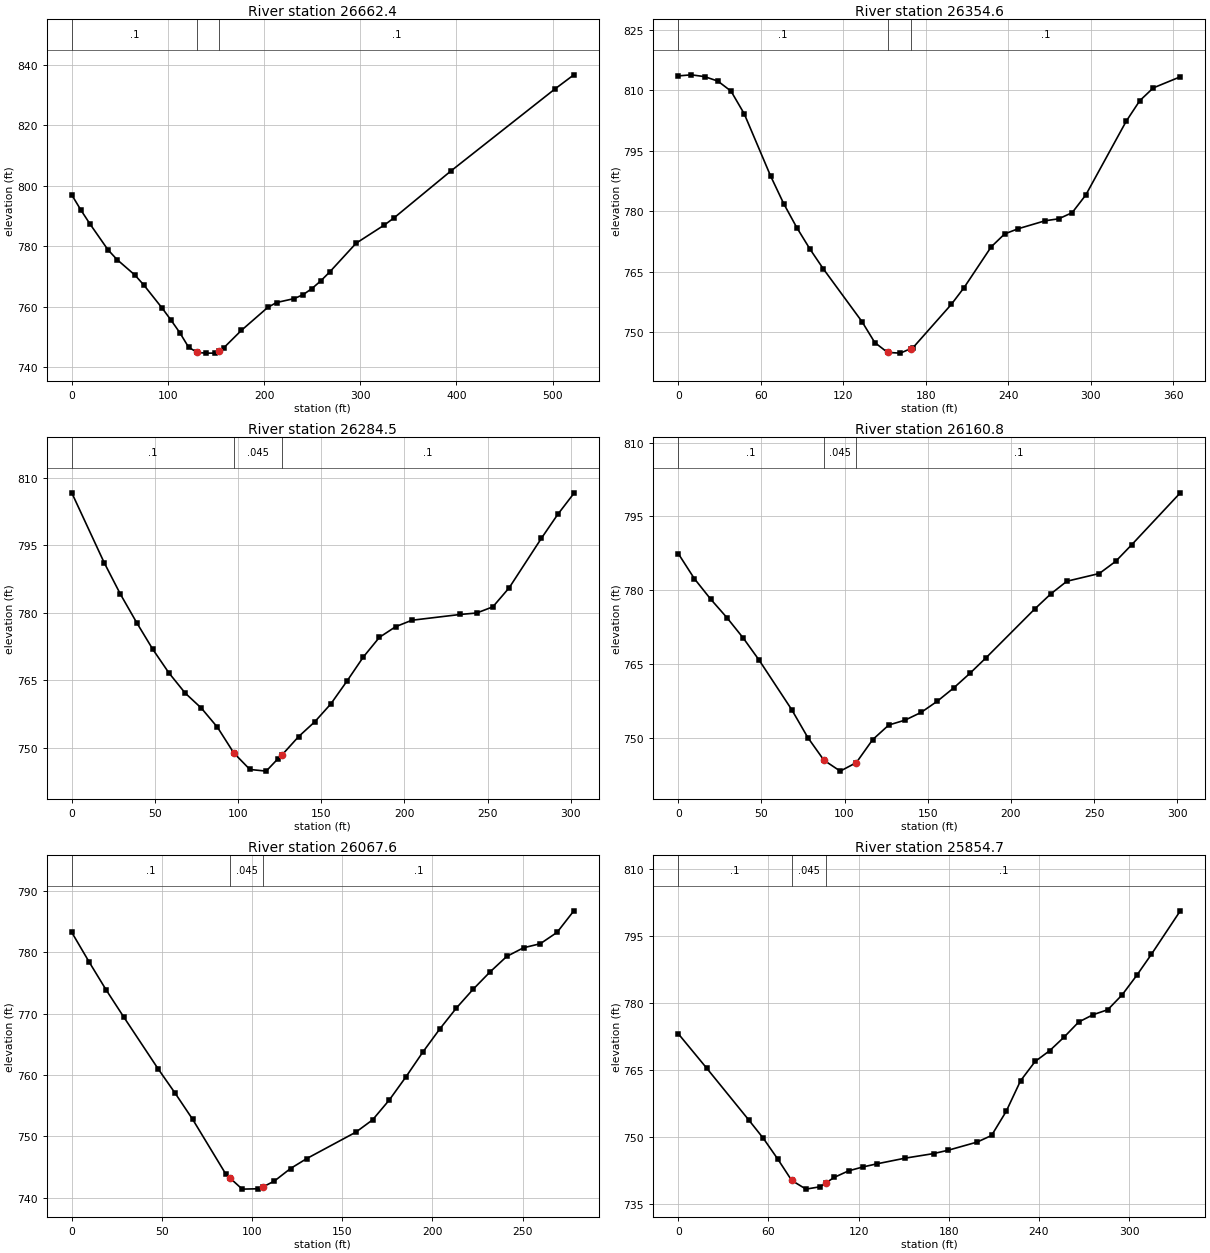
Type RM Length L Ch R = 1 ,26662.4 ,316.5,307.9,299.3
XS GIS Cut Line= 5
     1845912.279      541992.489     1845825.039      542027.645
     1845716.966      542045.874      1845625.82      542032.853
     1845447.435      542172.176
#Sta/Elev= 30
       0  796.92     9.4  791.96    18.8  787.37    37.6  778.79      47  775.56
    65.8  770.37    75.2  767.02    94.1  759.44   103.2  755.52   112.3  751.38
   121.5  746.55   130.6  744.81   139.7   744.6   148.9   744.6   152.9  745.36
     158  746.33   176.3   752.1   203.7  759.69   212.9  761.33   231.3  762.63
   240.5  763.92   249.7  765.94   258.9  768.48   268.1  771.39   295.7  780.95
   325.2     787   335.1  789.32   394.1  804.79   502.4  831.94   522.1  836.63
#Mann= 3 , 0 , 0
       0      .1       0   130.6    .045       0   152.9      .1       0
Bank Sta=130.6,152.9
XS Rating Curve= 0 ,0
Exp/Cntr=0.3,0.1

Type RM Length L Ch R = 1 ,26354.6 ,71.1,70,68.9
XS GIS Cut Line= 4
     1845805.508      541651.343     1845714.362      541721.655
     1845634.935      541769.833     1845493.008      541837.541
#Sta/Elev= 30
       0  813.62     9.6  813.89    19.2  813.44    28.8  812.34    38.4  809.84
      48  804.22    67.2  788.77    76.7  781.92    86.3  775.92    95.9  770.58
   105.5  765.73   133.7  752.59     143   747.4   152.3  744.94   161.6  744.77
     169  745.86   170.8  746.12   198.7  756.88     208  761.06   227.7  771.16
   237.5  774.38   247.3  775.66     267  777.65   276.8  778.13   286.6  779.65
   296.5  784.03     326   802.4   335.8  807.46   345.6  810.64   365.3   813.4
#Mann= 3 , 0 , 0
       0      .1       0   152.3    .045       0     169      .1       0
Bank Sta=152.3,169
XS Rating Curve= 0 ,0
Exp/Cntr=0.3,0.1

Type RM Length L Ch R = 1 ,26284.5 ,123.7,123.7,123.7
XS GIS Cut Line= 2
       1845737.8      541618.661       1845487.8      541787.931
#Sta/Elev= 29
       0  806.64    19.5  791.12    29.2  784.16      39  777.83    48.7   771.9
    58.4  766.65    68.2  762.16    77.9  758.83    87.6  754.57    97.4  748.88
   107.1   745.2   116.9  744.83     124  747.59   126.4  748.42   136.4   752.5
   146.1  755.78   155.8  759.77   165.6  764.89   175.3  770.17     185  774.55
   194.8  776.92   204.5  778.34   233.7  779.63   243.5  779.95   253.2  781.32
     263  785.54   282.4  796.55   292.2  801.84   301.9  806.51
#Mann= 3 , 0 , 0
       0      .1       0    97.4    .045       0   126.4      .1       0
Bank Sta=97.4,126.4
XS Rating Curve= 0 ,0
Exp/Cntr=0.3,0.1

Type RM Length L Ch R = 1 ,26160.8 ,94.6,93.3,92.2
XS GIS Cut Line= 2
     1845646.523      541531.551     1845396.523      541700.822
#Sta/Elev= 26
       0  787.45     9.7  782.34    19.5  778.18    29.2  774.45      39  770.32
    48.7  765.76    68.2  755.75    77.9  750.07    87.6  745.46    97.4  743.24
   107.1  744.97   116.9  749.63   126.6  752.61   136.4   753.6   146.1  755.18
   155.8  757.45   165.6  760.13   175.3  763.08     185  766.24   214.3  776.16
     224  779.24   233.7  781.82   253.2  783.39     263  785.85   272.7  789.24
   301.9  799.78
#Mann= 3 , 0 , 0
       0      .1       0    87.6    .045       0   107.1      .1       0
Bank Sta=87.6,107.1
XS Rating Curve= 0 ,0
Exp/Cntr=0.3,0.1

Type RM Length L Ch R = 1 ,26067.6 ,217.6,212.9,207.8
XS GIS Cut Line= 4
     1845575.039      541454.728     1845517.747       541505.51
     1845460.456      541548.478     1845382.331      541652.645
#Sta/Elev= 29
       0  783.24     9.6  778.43    19.1  773.84    28.7   769.5    47.8  761.03
    57.4  756.99      67  752.78    85.5   743.8      88  743.13    94.5  741.39
   103.4  741.45  106.29  741.79   112.4  742.72   121.3  744.75   130.3  746.37
   157.5  750.67   166.8  752.68   176.1  755.93   185.4  759.73   194.7  763.74
     204  767.47   213.3  770.92   222.6  773.98   231.9  776.78   241.2  779.32
   250.5  780.73   259.8  781.39   269.1  783.24   278.4  786.75
#Mann= 3 , 0 , 0
       0      .1       0      88    .045       0  106.29      .1       0
Bank Sta=88,106.29
XS Rating Curve= 0 ,0
Exp/Cntr=0.3,0.1

Type RM Length L Ch R = 1 ,25854.7 ,278.2,276.8,274.7
XS GIS Cut Line= 3
     1845403.164      541308.895     1845292.487      541437.801
     1845231.289      541590.145
#Sta/Elev= 30
       0  773.14    18.9  765.43    47.2   753.7    56.6  749.71    66.1  745.12
    75.5  740.27      85  738.32    94.4  738.85    98.6  739.79   103.8  740.95
   113.3  742.41   122.7  743.27   132.1  743.98     151  745.26   169.9  746.28
   179.6  747.03   198.9  748.86   208.5  750.34   218.2  755.72   227.8   762.6
   237.5  766.92   247.2  769.34   256.8  772.39   266.5  775.76   276.1   777.4
   285.8   778.5   295.4  781.84   305.1   786.2   314.8  790.89   334.1  800.66
#Mann= 3 , 0 , 0
       0      .1       0    75.5    .045       0    98.6      .1       0
Bank Sta=75.5,98.6
XS Rating Curve= 0 ,0
Exp/Cntr=0.3,0.1

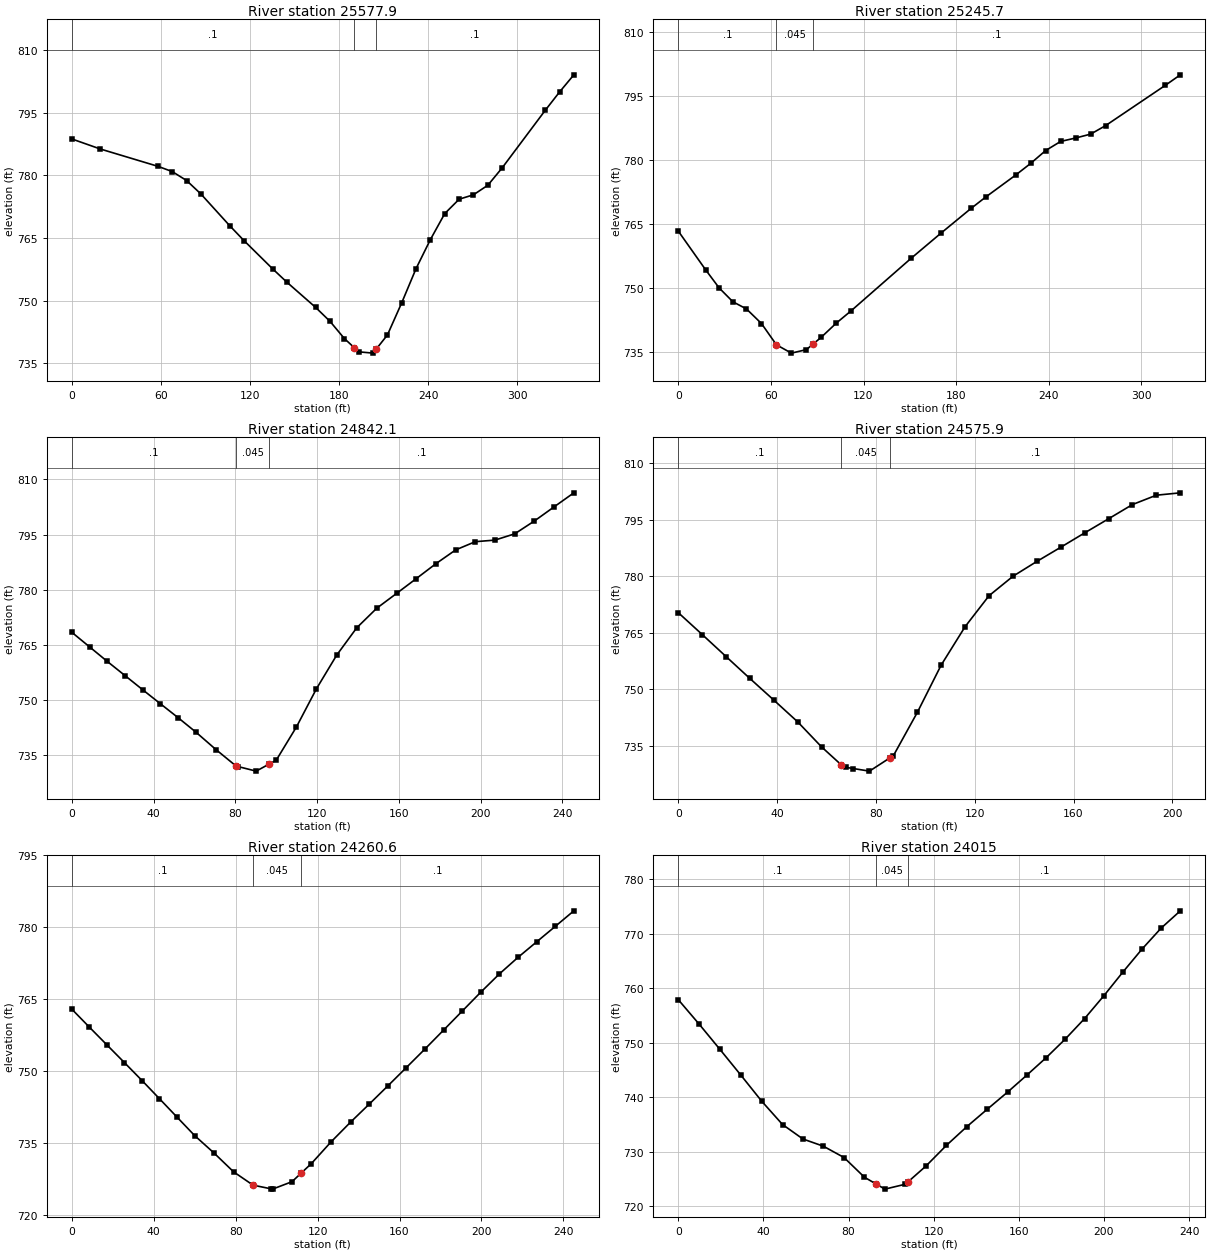
Type RM Length L Ch R = 1 ,25577.9 ,333.5,332.2,330.5
XS GIS Cut Line= 2
     1845228.685      541200.822     1845028.164      541472.958
#Sta/Elev= 29
       0  788.71    19.3  786.29      58  782.15    67.6   780.9    77.3  778.75
    86.9  775.54   106.2  767.98   115.9  764.38   135.2  757.61   144.9  754.38
   164.2  748.36   173.8  745.05   183.5  740.92   190.1  738.75   193.2  737.73
   202.8  737.42   205.1  738.45   212.5  741.77   222.1  749.45   231.8  757.68
   241.4  764.59   251.1  770.84   260.8  774.28   270.4  775.33   280.1  777.62
   289.7  781.76   318.7  795.54   328.4  799.96     338  804.06
#Mann= 3 , 0 , 0
       0      .1       0   190.1    .045       0   205.1      .1       0
Bank Sta=190.1,205.1
XS Rating Curve= 0 ,0
Exp/Cntr=0.3,0.1

Type RM Length L Ch R = 1 ,25245.7 ,405.4,403.6,402
XS GIS Cut Line= 3
     1844970.872      541030.249     1844960.456      541073.218
     1844809.414      541310.197
#Sta/Elev= 26
       0  763.39    17.7  754.33    26.5  750.06    35.4  746.82    44.2  745.14
    53.9  741.73    63.6  736.74    73.3  734.79      83  735.61    87.2  736.87
    92.7  738.53   102.4  741.83     112  744.71   150.8  756.99   170.2   762.9
   189.6  768.67   199.3  771.39   218.6  776.51   228.3  779.24     238  782.25
   247.7  784.38   257.4  785.18   267.1  786.09   276.8  788.08   315.5  797.52
   325.2  799.98
#Mann= 3 , 0 , 0
       0      .1       0    63.6    .045       0    87.2      .1       0
Bank Sta=63.6,87.2
XS Rating Curve= 0 ,0
Exp/Cntr=0.3,0.1

Type RM Length L Ch R = 1 ,24842.1 ,277.7,266.2,254.3
XS GIS Cut Line= 4
     1844595.872      540901.343     1844572.435      540957.333
     1844530.768      541035.458     1844515.143       541130.51
#Sta/Elev= 29
       0  768.47     8.7   764.5    17.3  760.58      26  756.72    34.7  752.85
    43.4  749.03      52  745.27    60.7  741.35    70.5  736.62    80.4  732.12
    81.4  731.98    90.2  730.75    96.4  732.62     100   733.7   109.9  742.75
   119.7  753.13   129.6  762.26   139.4  769.68   149.2     775   158.9  779.02
   168.5  783.03   178.1  787.08   187.8  790.84   197.4  793.07     207   793.5
   216.7  795.21   226.3  798.69   235.9  802.51   245.6  806.34
#Mann= 3 , 0 , 0
       0      .1       0    80.4    .045       0    96.4      .1       0
Bank Sta=80.4,96.4
XS Rating Curve= 0 ,0
Exp/Cntr=0.3,0.1

Type RM Length L Ch R = 1 ,24575.9 ,319.8,315.3,310.9
XS GIS Cut Line= 2
     1844295.091      540867.489       1844300.3      541070.614
#Sta/Elev= 25
       0  770.37     9.7  764.56    19.4  758.69      29   752.9    38.7  747.16
    48.4  741.36      58  734.76   65.99  729.99    67.7  729.35    70.8  729.02
    77.4  728.33    85.8   731.9    87.1  732.45    96.8  743.95   106.4  756.44
   116.1  766.64   125.8  774.86   135.5  780.02   145.1  783.93   154.8   787.7
   164.5  791.52   174.2  795.27   183.8  799.02   193.5  801.51   203.2  802.14
#Mann= 3 , 0 , 0
       0      .1       0   65.99    .045       0    85.8      .1       0
Bank Sta=65.99,85.8
XS Rating Curve= 0 ,0
Exp/Cntr=0.3,0.1

Type RM Length L Ch R = 1 ,24260.6 ,247.9,245.6,243.3
XS GIS Cut Line= 4
     1843976.081      540903.947     1843978.685      540963.843
     1843995.612      541038.062     1844055.508      541129.208
#Sta/Elev= 30
       0  762.91     8.6  759.14    17.1  755.46    25.7  751.74    34.3  747.99
    42.8   744.2    51.4  740.34      60  736.49    69.5  732.83      79  728.92
    88.5  726.14    97.1  725.39      98  725.31   107.5  726.86   112.1   728.7
     117  730.66   126.6  735.19   136.1   739.3   145.2  743.06   154.2  746.83
   163.3  750.69   172.4  754.57   181.5  758.52   190.6  762.49   199.7  766.46
   208.8  770.28   217.9  773.74     227  776.98     236  780.18   245.1  783.44
#Mann= 3 , 0 , 0
       0      .1       0    88.5    .045       0   112.1      .1       0
Bank Sta=88.5,112.1
XS Rating Curve= 0 ,0
Exp/Cntr=0.3,0.1

Type RM Length L Ch R = 1 ,24015   ,349.1,357.6,364.5
XS GIS Cut Line= 4
      1843719.57      540970.353     1843733.893      541017.228
     1843767.747      541117.489      1843775.56      541198.218
#Sta/Elev= 28
       0  757.91     9.8  753.42    19.6  748.77    29.4  744.06    39.2  739.27
      49  734.98    58.6  732.32    68.2     731    77.9  728.92    87.5   725.3
    93.1  724.03    97.1  723.12   106.7  724.02   108.1   724.5   116.4  727.36
     126  731.15   135.6  734.59   145.2  737.79   154.8  740.95   163.8  744.05
   172.9  747.26   181.9  750.69   190.9  754.42   199.9  758.58   208.9  762.96
   217.9  767.18   226.9  771.04   235.9  774.21
#Mann= 3 , 0 , 0
       0      .1       0    93.1    .045       0   108.1      .1       0
Bank Sta=93.1,108.1
XS Rating Curve= 0 ,0
Exp/Cntr=0.3,0.1