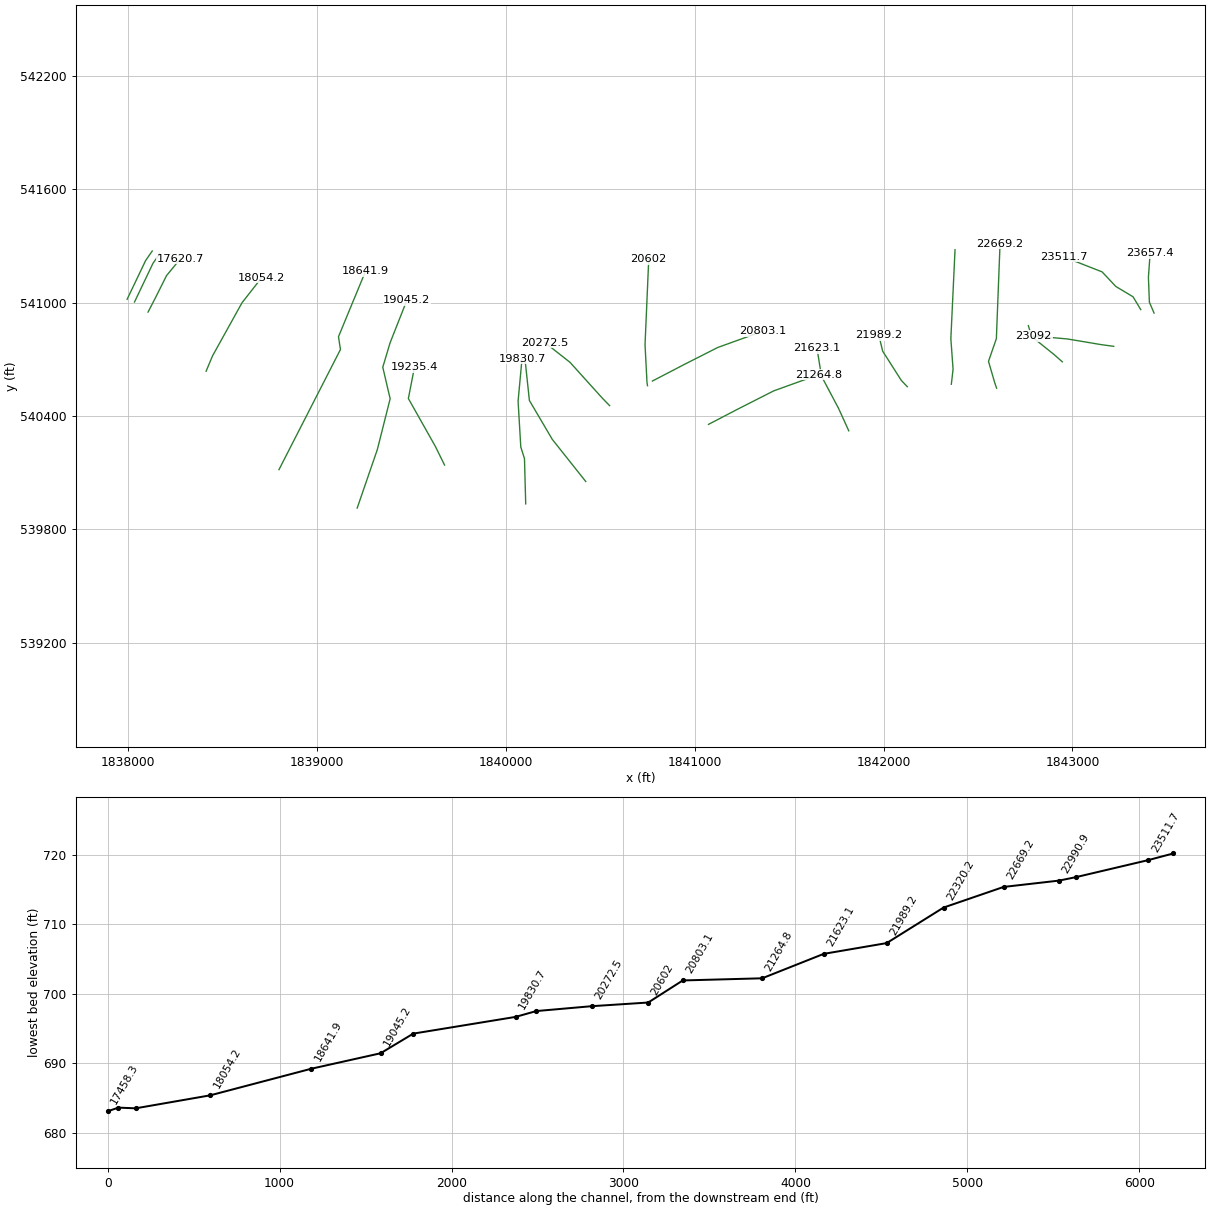
HEC-RAS study WILLSCK.prj: WILLSCK

--- WILLSCK.g01 (geometry) --- (continued)

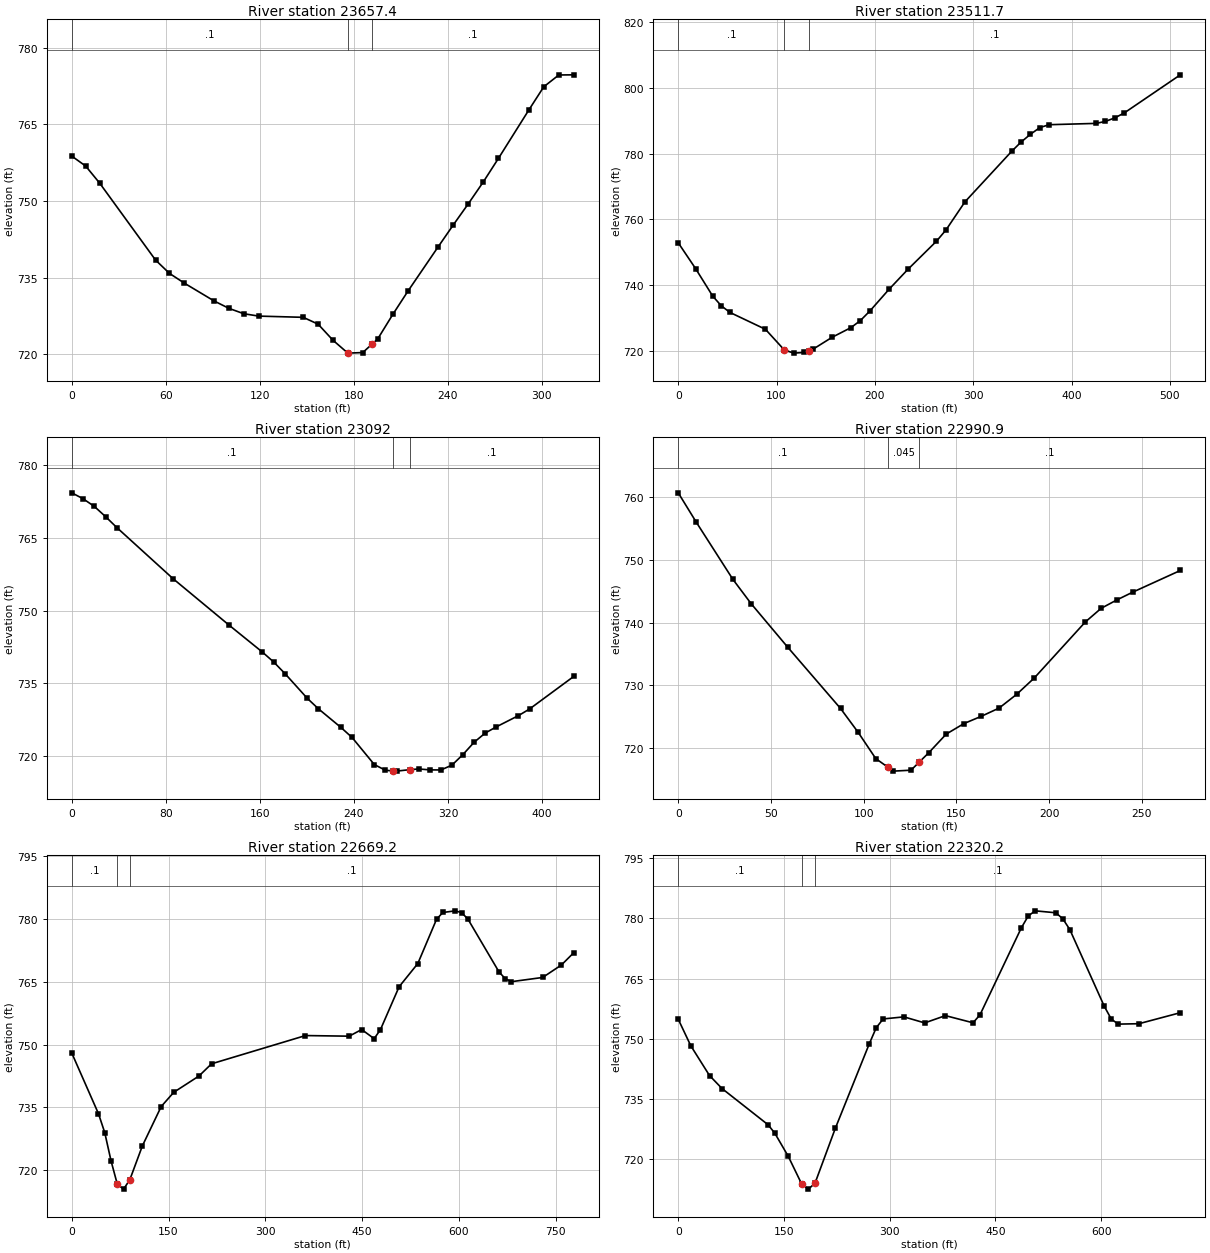
Type RM Length L Ch R = 1 ,23657.4 ,122.3,145.7,171.1
XS GIS Cut Line= 4
      1843431.81      540944.312      1843407.07      541001.603
     1843401.862      541134.416     1843410.977      541259.416
#Sta/Elev= 28
       0  758.81     8.9  756.85    17.8  753.52    53.5  738.45    62.4  735.84
    71.9  733.93    90.9  730.44   100.4  728.99   109.9  727.94   119.4  727.48
   147.8  727.24   157.3   725.9   166.8  722.75   176.3  720.23   185.8  720.34
   191.7  721.98   195.3  722.98     205  727.81   214.6  732.34   233.9  741.02
   243.5  745.28   253.2  749.47   262.8  753.76   272.4  758.34   291.7  767.76
   301.4  772.38     311  774.69   320.6  774.72
#Mann= 3 , 0 , 0
       0      .1       0   176.3    .045       0   191.7      .1       0
Bank Sta=176.3,191.7
XS Rating Curve= 0 ,0
Exp/Cntr=0.3,0.1

Type RM Length L Ch R = 1 ,23511.7 ,400.8,419.7,454.9
XS GIS Cut Line= 5
     1843361.438      540962.516      1843320.64      541030.225
     1843229.494      541084.912     1843156.577      541162.169
     1842952.584       541242.03
#Sta/Elev= 30
       0  752.85    17.6  745.02    35.1  736.61    43.9  733.64    52.7  731.64
    88.7  726.52     108  720.19   117.7  719.27   127.4  719.47   132.7  720.01
     137  720.45   156.4  724.08   175.7  727.04   185.3   729.2     195  732.12
   214.3  738.67   233.6  744.78   262.6  753.33   272.3  756.76   291.6  765.32
   339.2  780.72   348.7  783.52   358.2  785.88   367.8  787.93   377.3  788.79
   424.9  789.19   434.4  789.79     444  790.87   453.5  792.35   510.6  803.97
#Mann= 3 , 0 , 0
       0      .1       0     108    .045       0   132.7      .1       0
Bank Sta=108,132.7
XS Rating Curve= 0 ,0
Exp/Cntr=0.3,0.1

Type RM Length L Ch R = 1 ,23092   ,123.2,101,61.3
XS GIS Cut Line= 4
     1843218.268      540768.313     1843151.862      540777.428
     1842973.477      540807.376     1842795.091      540823.001
#Sta/Elev= 30
       0  774.32     9.6   773.1    19.2  771.51    28.7  769.41    38.3  767.15
    86.1  756.59   133.7     747   162.2   741.4   171.8  739.35   181.3  736.98
   200.3  731.86   209.8  729.69   228.9  725.85   238.4  723.77   257.3  718.18
   266.8  716.99   272.8  716.88   276.2  716.82   287.8  717.13     295  717.27
   304.5  717.08   313.9  717.06   323.3  718.05   332.7  720.25   342.2  722.79
   351.6  724.68     361  725.96   379.9  728.29   389.3  729.65     427   736.4
#Mann= 3 , 0 , 0
       0      .1       0   272.8    .045       0   287.8      .1       0
Bank Sta=272.8,287.8
XS Rating Curve= 0 ,0
Exp/Cntr=0.3,0.1

Type RM Length L Ch R = 1 ,22990.9 ,335.6,321.7,307.6
XS GIS Cut Line= 4
     1842946.133      540686.499     1842901.862      540725.562
     1842783.372      540820.614     1842766.445      540877.905
#Sta/Elev= 24
       0  760.71     9.8  755.99    29.5  746.89    39.4  742.99      59  736.09
    87.5  726.31      97   722.5   106.5  718.31  112.93  716.96     116  716.31
   125.5  716.46     130  717.77     135  719.22   144.5  722.22     154  723.89
   163.5  725.07     173  726.37   182.5  728.57     192  731.18   219.5  740.11
     228  742.28   236.6  743.64   245.1  744.87   270.7  748.32
#Mann= 3 , 0 , 0
       0      .1       0  112.93    .045       0     130      .1       0
Bank Sta=112.93,130
XS Rating Curve= 0 ,0
Exp/Cntr=0.3,0.1

Type RM Length L Ch R = 1 ,22669.2 ,354.5,349.1,343.8
XS GIS Cut Line= 5
     1842598.477      540547.176      1842588.06      540577.124
     1842555.508      540689.103     1842597.175      540808.895
     1842616.706      541311.499
#Sta/Elev= 30
       0  747.96    41.4  733.44    51.1  728.92    60.9  722.14    70.6  716.56
    80.3   715.4      90  717.66   109.4  725.74   138.6  735.16   158.1  738.57
   197.1  742.46   216.6  745.38   362.2  752.14   429.9  751.99   449.3  753.58
   468.6   751.4   478.3  753.53   507.3  763.82   536.3  769.37   565.3  779.95
     575  781.58   594.4  781.98     604  781.55   613.7  780.06   662.1  767.37
   671.7  765.76   681.4  765.03   729.8  766.04   758.8  769.02   778.1  771.98
#Mann= 3 , 0 , 0
       0      .1       0    70.6    .045       0      90      .1       0
Bank Sta=70.6,90
XS Rating Curve= 0 ,0
Exp/Cntr=0.3,0.1

Type RM Length L Ch R = 1 ,22320.2 ,319.3,331,341.8
XS GIS Cut Line= 4
     1842358.893       540568.01     1842368.008      540647.437
     1842356.289      540808.895     1842378.425      541278.947
#Sta/Elev= 30
       0  754.84    17.8  748.22    44.4  740.78    62.2  737.53   127.6  728.48
   137.1  726.37   156.1  720.62   175.2  713.69   184.7  712.43   194.1  713.92
   222.8  727.57   271.2  748.76     281  752.74   290.8  754.91   320.3  755.43
   349.7  753.92   379.1  755.74   418.3  753.95   428.1  755.92   486.9  777.68
   496.7  780.63   506.5   781.9   535.9  781.41   545.7   779.9   555.6  777.23
   604.6  758.04   614.4   754.9   624.2  753.62   653.6  753.72   712.4  756.47
#Mann= 3 , 0 , 0
       0      .1       0   175.2    .045       0   194.1      .1       0
Bank Sta=175.2,194.1
XS Rating Curve= 0 ,0
Exp/Cntr=0.3,0.1

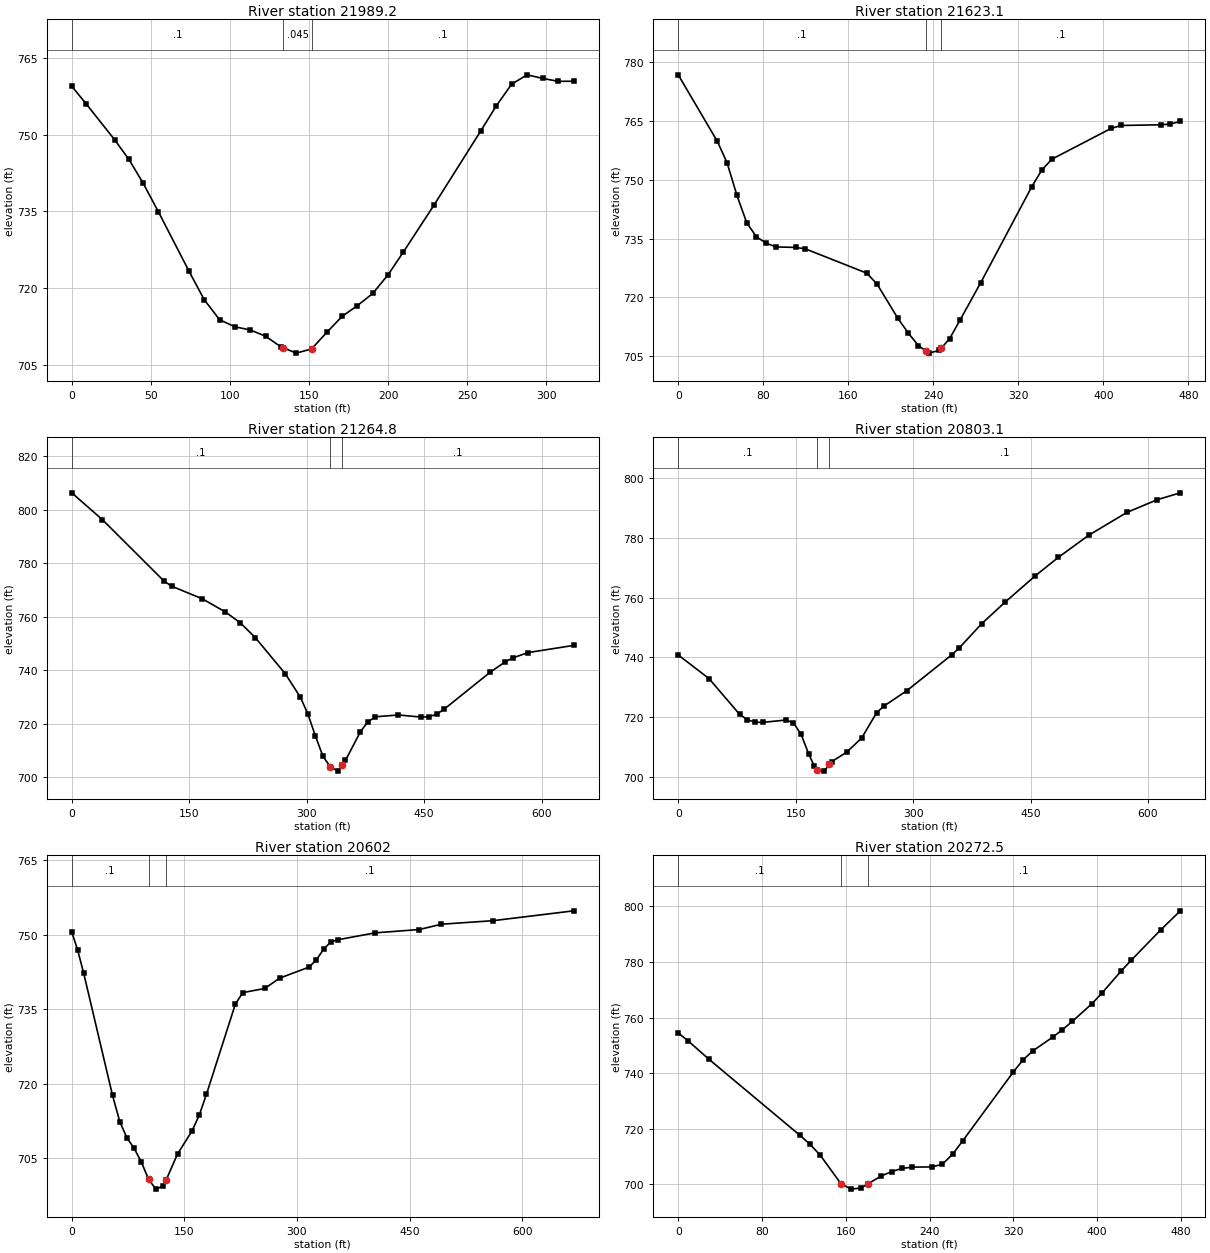
Type RM Length L Ch R = 1 ,21989.2 ,368.1,366.1,364.2
XS GIS Cut Line= 4
      1842125.82      540554.989      1842094.57      540587.541
     1841995.612      540742.489     1841974.779      540828.426
#Sta/Elev= 30
       0  759.46       9  756.06    27.1     749    36.1  745.17    45.1  740.53
    54.8   734.9    74.2  723.27    83.8  717.72    93.5  713.82   103.2  712.45
   112.9  711.83   122.5  710.62   132.2  708.54   133.8  708.34   141.9  707.31
   151.6  708.13   161.2  711.36   170.9  714.49   180.6   716.6   190.3  718.98
     200  722.64   209.6  727.06     229  736.24   258.4  750.65   268.3  755.59
   278.1  759.88   287.9  761.69   297.8  760.98   307.6  760.42   317.4  760.44
#Mann= 3 , 0 , 0
       0      .1       0   133.8    .045       0   151.6      .1       0
Bank Sta=133.8,151.6
XS Rating Curve= 0 ,0
Exp/Cntr=0.3,0.1

Type RM Length L Ch R = 1 ,21623.1 ,398,358.3,317.5
XS GIS Cut Line= 4
     1841815.925      540321.916     1841762.539      540439.103
     1841671.393      540610.978     1841647.956      540758.114
#Sta/Elev= 30
       0  776.76    36.8  759.78      46  754.27    55.2  746.02    64.4  739.04
    73.6  735.42    82.8   733.8      92  732.85   110.4  732.73   119.6  732.36
   177.4  726.16   187.1  723.34   206.6  714.64   216.3  710.91     226  707.66
   232.6  706.38   235.8  705.76   245.5  706.45   247.6  707.09   255.2  709.41
     265  714.15   284.4  723.66   332.6  748.23     342  752.46   351.3  755.21
   407.1  763.08   416.4  763.84   453.7  764.01     463   764.2   472.3   764.9
#Mann= 3 , 0 , 0
       0      .1       0   232.6    .045       0   247.6      .1       0
Bank Sta=232.6,247.6
XS Rating Curve= 0 ,0
Exp/Cntr=0.3,0.1

Type RM Length L Ch R = 1 ,21264.8 ,462.7,461.7,461.3
XS GIS Cut Line= 4
     1841073.737       540355.77     1841239.102      540441.708
     1841418.789      540532.853      1841657.07      540618.791
#Sta/Elev= 30
       0  806.28    39.2  796.22   117.7  773.32   127.5  771.38   166.7  766.66
     196  761.78   215.1  757.72   234.3  752.19   272.7  738.63   291.9  729.91
   301.5  723.62   311.1  715.42   320.7  707.85   330.3  703.81   339.9  702.24
   345.7  704.64   349.5  706.22   368.7  717.01   378.2  720.68   387.8  722.55
   417.1  723.24   446.3  722.44     456  722.58   465.8  723.48   475.5  725.38
     534  739.13   553.5   743.1   563.2  744.55   582.7  746.56   641.2  749.25
#Mann= 3 , 0 , 0
       0      .1       0   330.3    .045       0   345.7      .1       0
Bank Sta=330.3,345.7
XS Rating Curve= 0 ,0
Exp/Cntr=0.3,0.1

Type RM Length L Ch R = 1 ,20803.1 ,170.2,201,232.1
XS GIS Cut Line= 4
     1840776.862      540584.937     1840942.227      540670.874
     1841121.914       540762.02     1841360.195      540847.958
#Sta/Elev= 30
       0  740.79    39.2  732.92    78.5  720.89    88.3  719.13    98.1   718.3
   107.9  718.24   137.3  719.02   147.1  718.13   156.9  714.22   166.7  707.63
   173.6   703.7   176.6  702.39   186.4  701.93   193.1  704.16     196  705.12
   215.1  708.26   234.3  713.02   253.5  721.54   263.1  723.77   291.9  728.83
   349.5  740.88   359.1  743.21   387.8  751.32   417.1  758.38     456  767.28
   485.3  773.42   524.2  780.85     573  788.48   611.9  792.76   641.2  795.04
#Mann= 3 , 0 , 0
       0      .1       0   176.6    .045       0   193.1      .1       0
Bank Sta=176.6,193.1
XS Rating Curve= 0 ,0
Exp/Cntr=0.3,0.1

Type RM Length L Ch R = 1 ,20602   ,314.1,329.6,344.9
XS GIS Cut Line= 4
      1840750.82      540560.197     1840748.216      540575.822
       1840737.8      540777.645     1840757.331      541228.166
#Sta/Elev= 30
       0  750.57     7.9  746.91    15.8  742.32    54.3  717.64      64  712.34
    73.6  709.05    83.2  706.96    92.8  704.17   102.4   700.7   112.1  698.75
   121.7  699.36     126  700.68   140.9  705.84   160.2  710.46   169.8  713.66
   179.4  717.85   217.9  736.03   227.7  738.36   257.1   739.2   276.8  741.27
     316   743.5   325.8  744.94   335.6  747.13   345.4  748.61   355.2  749.04
   404.2  750.41     463  751.08   492.4  752.15     561  752.86   668.9  754.85
#Mann= 3 , 0 , 0
       0      .1       0   102.4    .045       0     126      .1       0
Bank Sta=102.4,126
XS Rating Curve= 0 ,0
Exp/Cntr=0.3,0.1

Type RM Length L Ch R = 1 ,20272.5 ,325.9,321.5,316.9
XS GIS Cut Line= 4
       1840550.3      540454.728     1840509.935      540496.395
     1840340.664      540683.895     1840207.852      540788.062
#Sta/Elev= 30
       0  754.44     9.7  751.52      29  745.08   116.3  717.56     126   714.3
   135.7  710.39   155.2  700.24   164.9  698.22   174.6  698.62   180.8  700.07
     194  702.98   203.8  704.54   213.5  705.66   223.2  706.14   242.6  706.22
   252.3  707.23     262  710.78   271.8  715.69     320  740.43   329.4  744.84
   338.8  748.06   357.5  752.93   366.9  755.64   376.3  758.63     395  764.97
   404.4  768.73   423.1  776.83   432.5  780.62   460.6  791.54   479.4  798.43
#Mann= 3 , 0 , 0
       0      .1       0   155.2    .045       0   180.8      .1       0
Bank Sta=155.2,180.8
XS Rating Curve= 0 ,0
Exp/Cntr=0.3,0.1

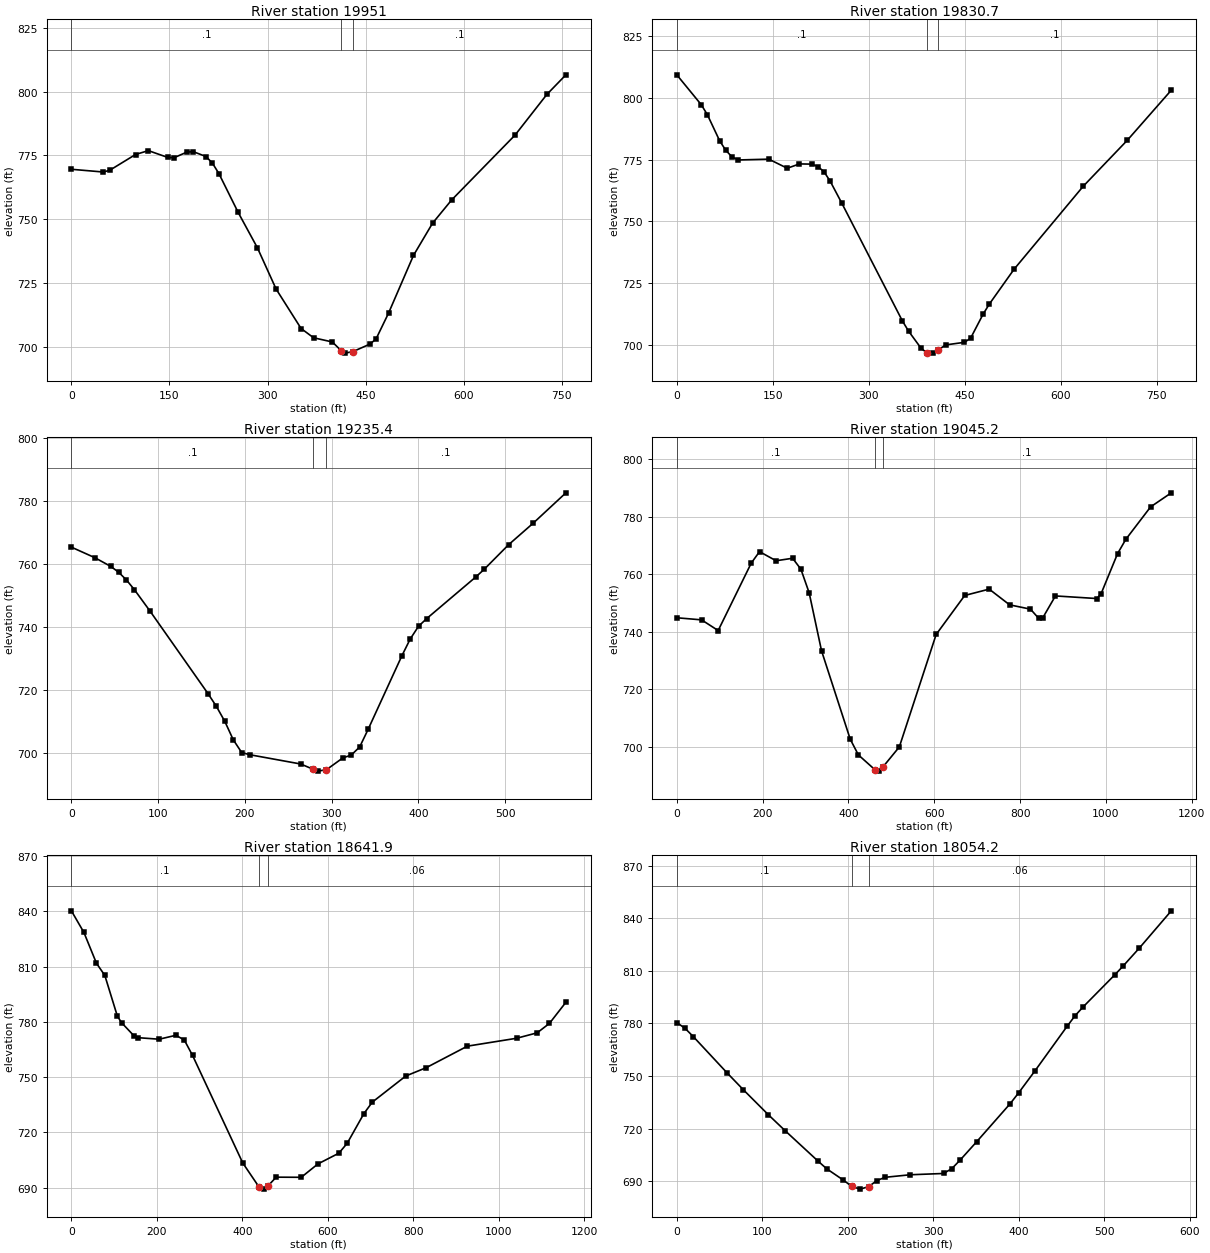
Type RM Length L Ch R = 1 ,19951   ,131.7,120.3,109.1
XS GIS Cut Line= 4
     1840423.997      540053.687     1840246.914      540276.343
      1840125.82      540482.072     1840101.081      540713.843
#Sta/Elev= 30
       0  769.56      49  768.48    58.9  769.21    98.1  775.35   117.7  776.87
   147.2  774.22     157   774.1   176.6  776.28   186.4  776.46     206  774.54
   215.8  771.92   225.6  767.88   255.1  752.64   284.5  738.79   313.1  722.63
   351.3  707.17   370.4  703.54   399.1  701.89   412.7  698.47   418.2  697.52
  430.13  698.07   456.4  701.03   465.9  703.05     485  713.16   523.2  735.81
   552.4  748.44   581.5  757.52   678.6  782.97   727.2  798.89   756.3  806.57
#Mann= 3 , 0 , 0
       0      .1       0   412.7    .045       0  430.13      .1       0
Bank Sta=412.7,430.13
XS Rating Curve= 0 ,0
Exp/Cntr=0.3,0.1

Type RM Length L Ch R = 1 ,19830.7 ,583.9,595.4,605.5
XS GIS Cut Line= 5
     1840106.289      539935.197     1840099.779       540174.78
     1840080.247      540235.978     1840065.925      540478.166
     1840086.758      540703.426
#Sta/Elev= 30
       0  809.38    38.4  797.23    47.9  793.17    67.1   782.6    76.7  778.76
    86.3  776.15    95.9   774.9   143.8  775.23   172.6  771.55   191.7   773.3
   210.9  773.22   220.5  772.25   230.1  770.11   239.7   766.3     258  757.33
   352.4  709.78   362.1  705.61   381.6   698.7   391.2  696.68     401  696.72
     408   697.9   420.4  700.02   449.5  701.05   459.2  702.77   478.6  712.44
   488.3  716.52   527.1  730.68     635  764.23   703.9  782.86   772.7  803.16
#Mann= 3 , 0 , 0
       0      .1       0   391.2    .045       0     408      .1       0
Bank Sta=391.2,408
XS Rating Curve= 0 ,0
Exp/Cntr=0.3,0.1

Type RM Length L Ch R = 1 ,19235.4 ,207.6,190.2,173
XS GIS Cut Line= 4
     1839676.602      540140.926     1839628.425      540238.583
     1839485.195      540492.489     1839517.747      540659.155
#Sta/Elev= 30
       0  765.27    27.2  761.91    45.4  759.16    54.4  757.34    63.5  754.86
    72.6  751.81    90.7  744.99   157.5  718.85   167.2  714.79   176.9  710.04
   186.6  704.23   196.4  700.15   206.1  699.45   264.4  696.53     279  694.84
   283.8  694.27     294   694.7     313  698.46   322.7  699.36   332.4  701.93
   342.1  707.48     381  730.79   390.7  736.16   400.4  740.23   409.8  742.65
   466.4  755.84   475.9  758.22   504.2  766.06   532.5  772.87   570.2  782.49
#Mann= 3 , 0 , 0
       0      .1       0     279    .045       0     294      .1       0
Bank Sta=279,294
XS Rating Curve= 0 ,0
Exp/Cntr=0.3,0.1

Type RM Length L Ch R = 1 ,19045.2 ,408.7,403.3,397.7
XS GIS Cut Line= 6
     1839214.362      539913.062     1839321.133      540222.958
     1839388.841      540491.187     1839349.779      540657.853
     1839388.841      540788.062     1839477.383       541012.02
#Sta/Elev= 30
       0  744.81    57.8  744.08    96.4  740.36   173.5  763.83   192.8  767.82
   231.4  764.65   269.9  765.52   289.2  761.72   308.5  753.48   337.3  733.33
   404.1  702.58   423.2  697.08   461.3  691.99   470.9  691.44   480.4  692.89
   518.6  699.86   604.4  738.99     671  752.57     728  754.78   775.6  749.31
   824.2  747.81   843.6  744.58   853.3   744.9   882.4  752.41     979   751.5
   988.6  753.11  1027.1   767.1  1046.4   772.1  1104.2   783.4  1152.4  788.29
#Mann= 3 , 0 , 0
       0      .1       0   461.3    .045       0   480.4      .1       0
Bank Sta=461.3,480.4
XS Rating Curve= 0 ,0
Exp/Cntr=0.3,0.1

Type RM Length L Ch R = 1 ,18641.9 ,588,587.7,586.5
XS GIS Cut Line= 4
       1838800.3      540116.187      1839125.82      540751.603
     1839115.404      540819.312     1839258.633      541165.666
#Sta/Elev= 30
       0  840.25    29.3  828.51    58.7  811.78    78.2   805.2   107.6  783.08
   117.4  779.55   146.7  772.35   156.5   771.4   205.4  770.57   244.5   772.7
   264.1  770.18   283.6  761.74     401  703.42   438.4   690.6   449.9  689.21
   459.7  690.86   479.2   695.7   537.9  695.63     577   702.9   625.9  708.71
   645.5  714.12   684.6  730.23   704.2  736.42   782.4  750.59   830.5  755.14
   926.6   766.8  1041.9  771.09    1090  774.04  1118.8  779.18  1157.2  790.62
#Mann= 3 , 0 , 0
       0      .1       0   438.4    .045       0   459.7     .06       0
Bank Sta=438.4,459.7
XS Rating Curve= 0 ,0
Exp/Cntr=0.3,0.1

Type RM Length L Ch R = 1 ,18054.2 ,429.5,433.5,436.6
XS GIS Cut Line= 4
     1838414.883       540637.02     1838448.737      540717.749
     1838604.987      540998.999     1838709.154      541131.812
#Sta/Elev= 30
       0  780.51     9.7  777.18    19.4  772.42    58.4  751.96    77.8  742.13
     107  727.88   126.5  718.81   165.5  701.21   175.3  696.98   194.8  690.51
   204.5  686.95   214.3  685.38   224.2  686.76   233.8  690.24   243.5  692.13
   272.8  693.58   311.8  694.32   321.5  697.07   331.3     702   350.8  712.57
   389.8  734.21   399.5  740.27   418.7   752.9   456.2   778.3   465.5  784.34
   474.9  789.37   512.4  807.93   521.8  812.79   540.6  822.95   578.1   844.3
#Mann= 3 , 0 , 0
       0      .1       0   204.5    .045       0   224.2     .06       0
Bank Sta=204.5,224.2
XS Rating Curve= 0 ,0
Exp/Cntr=0.3,0.1

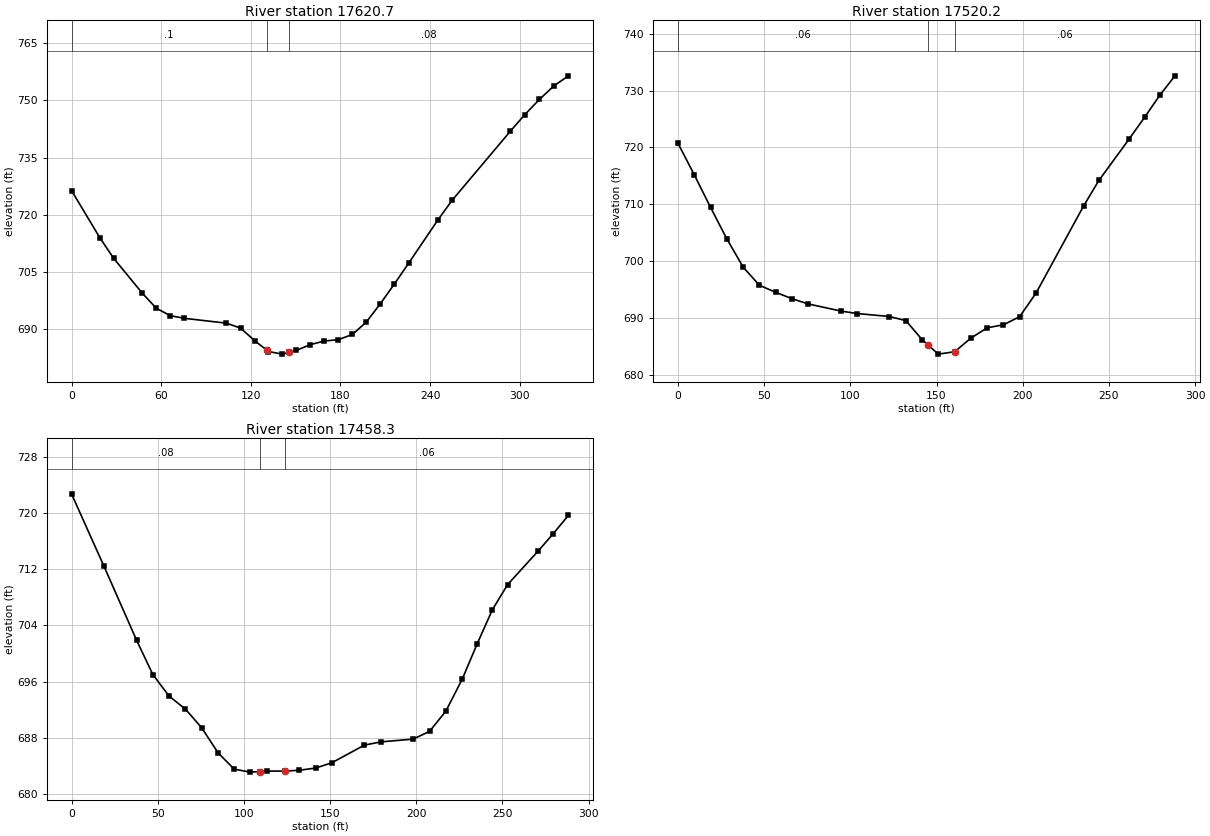
Type RM Length L Ch R = 1 ,17620.7 ,103.3,100.5,98.9
XS GIS Cut Line= 4
     1838107.546      540949.499     1838146.609       541025.02
     1838205.203      541142.207     1838279.421      541232.051
#Sta/Elev= 30
       0  726.37    18.9  714.03    28.3  708.56    47.2  699.56    56.7  695.54
    66.1  693.58    75.6  692.89   103.7  691.62   113.1  690.33   122.5  687.06
   130.7  684.53   131.8  684.19   141.2  683.51   145.7  683.99   150.5   684.5
   159.9  686.01   169.2  686.94   178.6   687.3     188  688.66   197.3  691.91
   206.7  696.72     216  701.83   225.8  707.42   245.2  718.66   254.9  723.88
   293.7   741.9   303.4  746.25   313.2  750.25   322.9  753.78   332.6  756.41
#Mann= 3 , 0 , 0
       0      .1       0   130.7    .045       0   145.7     .08       0
Bank Sta=130.7,145.7
XS Rating Curve= 0 ,0
Exp/Cntr=0.3,0.1

Type RM Length L Ch R = 1 ,17520.2 ,68.9,61.9,45.4
XS GIS Cut Line= 3
     1838035.932      541002.884     1838133.588      541207.312
     1838168.744      541258.093
#Sta/Elev= 28
       0  720.72     9.4  715.21    18.9  709.44    28.3  703.92    37.8  698.93
    47.2  695.74    56.6   694.5    66.1  693.37    75.5  692.45    94.4   691.2
   103.8  690.76   122.7  690.23   132.2  689.51   141.6  686.17   144.8   685.3
     151  683.61   160.5  684.03   169.9  686.42   179.4  688.25   188.8  688.77
   198.2   690.2   207.7  694.34   235.4  709.74   244.2  714.19   261.8   721.5
   270.7   725.3   279.5  729.17   288.3   732.6
#Mann= 3 , 0 , 0
       0     .06       0   144.8    .045       0   160.5     .06       0
Bank Sta=144.8,160.5
XS Rating Curve= 0 ,0
Exp/Cntr=0.3,0.1

Type RM Length L Ch R = 1 ,17458.3 ,50.3,57,71.7
XS GIS Cut Line= 3
     1837996.869      541017.207     1838094.526      541221.634
     1838129.682      541272.416
#Sta/Elev= 28
       0  722.77    18.9  712.41    37.8  701.87    47.2     697    56.6  693.93
    66.1  692.07    75.5  689.42      85  685.85    94.4  683.51   103.8  683.09
   109.1  683.17   113.3  683.24   124.1  683.24   132.2  683.36   141.6  683.67
     151  684.42   169.9  686.94   179.4   687.4   198.2   687.8   207.7   688.9
   217.1  691.76   226.6  696.31   235.4  701.42   244.2  706.26     253  709.83
   270.7  714.61   279.5   717.1   288.3   719.7
#Mann= 3 , 0 , 0
       0     .08       0   109.1    .045       0   124.1     .06       0
Bank Sta=109.1,124.1
XS Rating Curve= 0 ,0
Exp/Cntr=0.3,0.1