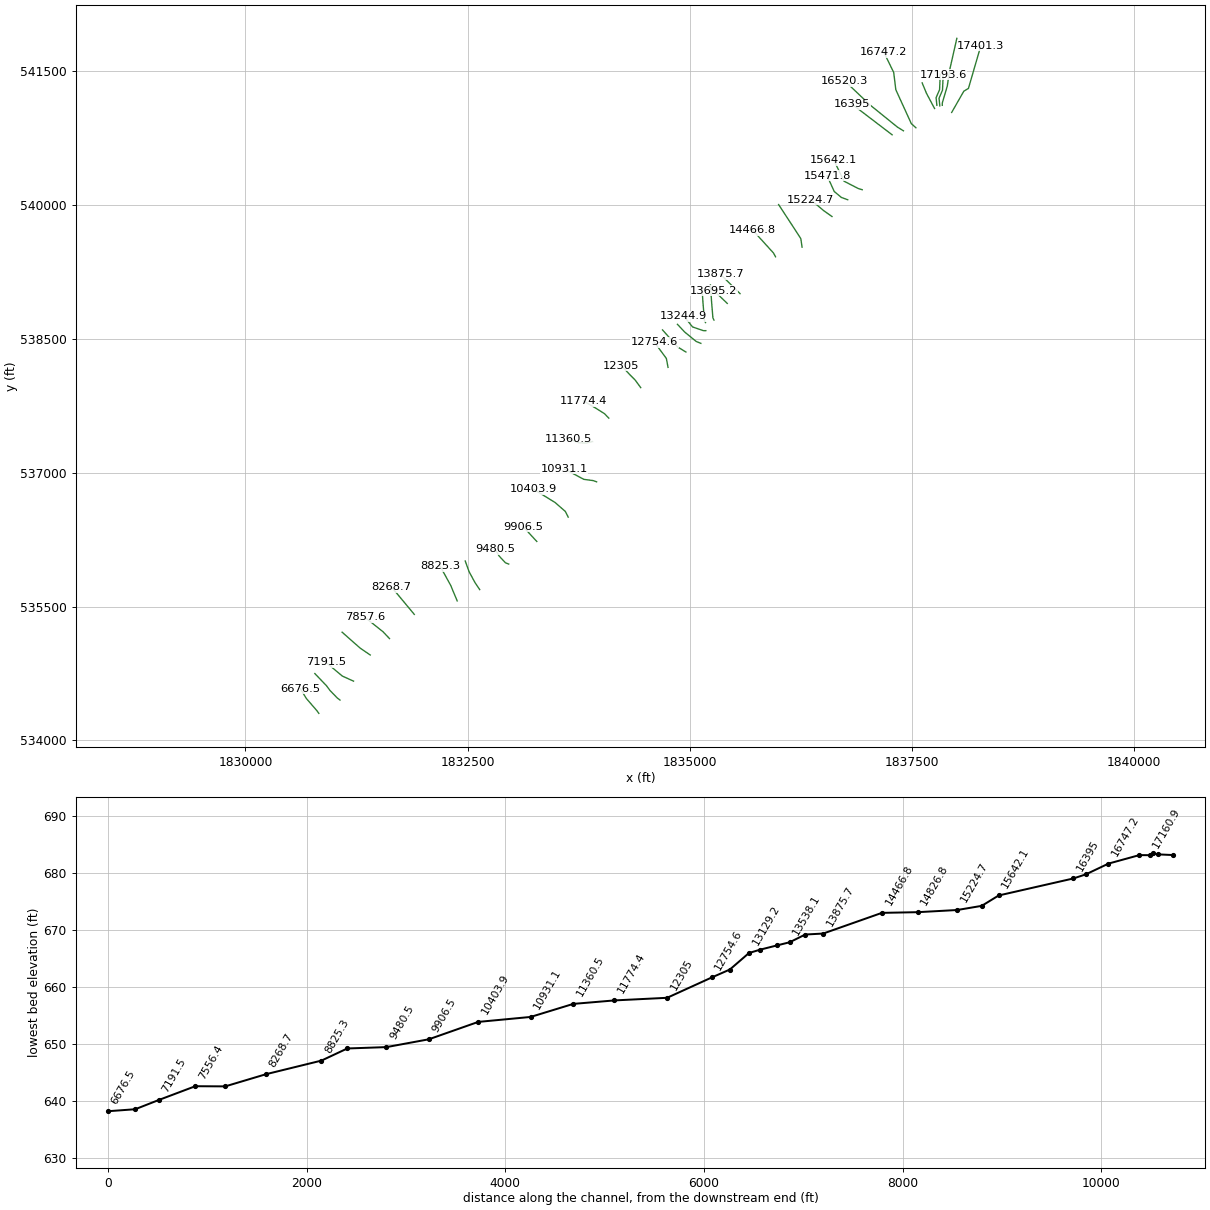
HEC-RAS study WILLSCK.prj: WILLSCK

--- WILLSCK.g01 (geometry) --- (continued)

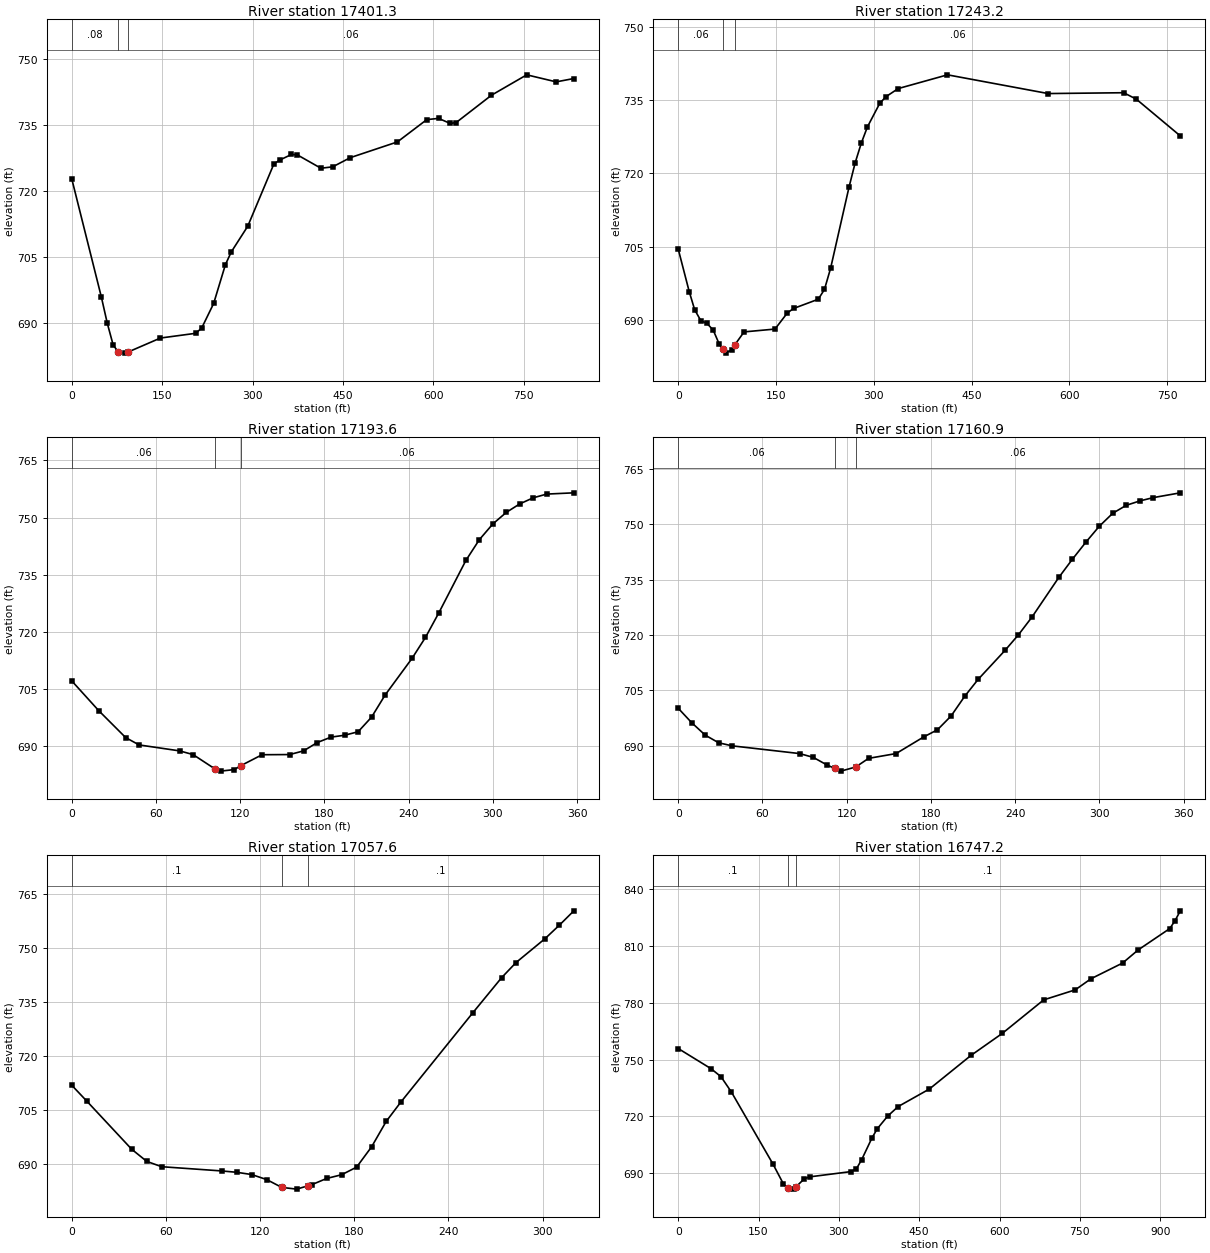
Type RM Length L Ch R = 1 ,17401.3 ,151.9,158.1,163.5
XS GIS Cut Line= 4
     1837949.994      541038.041     1838086.713      541276.322
     1838138.796      541307.572     1838278.293      541785.523
#Sta/Elev= 30
       0   722.7    49.1  695.86    58.9  689.92    68.7  684.95   77.27  683.35
    88.3   683.1    93.8  683.37   147.2  686.53     206  687.61   215.8  688.84
   235.5  694.38   255.1  703.24   264.9  706.13   292.1  711.94   335.5   726.1
   345.2  726.98   364.7  728.25   374.5  728.15   413.6  725.12   433.1  725.44
   462.4  727.53   540.5   731.1   589.3  736.17   608.8  736.45   628.3   735.3
   638.1  735.51   696.7  741.72   755.2  746.35   804.1  744.75   833.4  745.51
#Mann= 3 , 0 , 0
       0     .08       0   77.27    .045       0    93.8     .06       0
Bank Sta=77.27,93.8
XS Rating Curve= 0 ,0
Exp/Cntr=0.3,0.1

Type RM Length L Ch R = 1 ,17243.2 ,52.9,49.6,46.8
XS GIS Cut Line= 5
     1837844.265      541117.989     1837844.265      541143.162
     1837900.689      541334.134      1837926.73      541511.218
     1838008.328      541868.857
#Sta/Elev= 30
       0  704.48    16.8  695.82    25.2  692.09    34.7  689.85    44.1  689.29
    53.6  687.94    63.1     685   68.41  683.97    72.6  683.22    82.1  683.88
    86.6  684.89     101  687.56   148.4  688.14   167.4  691.44   176.9  692.35
   214.8  694.24   224.3  696.25   233.7  700.57     262  717.18   271.4  722.14
   280.8  726.17   290.2  729.48   309.1  734.29   318.5  735.64   337.4  737.31
     413  740.12   567.4  736.29   683.2  736.46   702.6  735.15   770.1  727.63
#Mann= 3 , 0 , 0
       0     .06       0   68.41    .045       0    86.6     .06       0
Bank Sta=68.41,86.6
XS Rating Curve= 0 ,0
Exp/Cntr=0.3,0.1

Type RM Length L Ch R = 1 ,17193.6 ,32.7,32.7,32.7
XS GIS Cut Line= 4
     1837816.487      541111.912     1837807.807       541197.85
     1837846.869      541288.128     1837854.682      541460.871
#Sta/Elev= 30
       0  707.09    19.2  699.28    38.4   692.2      48  690.27    76.8  688.71
    86.4  687.74  102.39  683.88     106  683.39   115.9   683.8   120.3   684.8
   135.6   687.7   155.2  687.74   165.1   688.7   174.9   690.9   184.7  692.32
   194.4  692.82     204  693.73   213.6  697.58   223.2  703.36   242.4     713
     252  718.52   261.6  725.03   280.8  738.74   290.4   744.2     300  748.32
   309.6  751.36   319.2  753.59   328.8  755.19   338.4  756.16   357.7  756.49
#Mann= 3 , 0 , 0
       0     .06       0  102.39    .045       0   120.3     .06       0
Bank Sta=102.39,120.3
XS Rating Curve= 0 ,0
Exp/Cntr=0.3,0.1

Type RM Length L Ch R = 1 ,17160.9 ,82.5,103.3,123.6
XS GIS Cut Line= 4
     1837783.501      541117.989     1837774.821      541203.926
     1837813.883      541294.204     1837821.696      541466.947
#Sta/Elev= 30
       0  700.11     9.6   696.2    19.2  692.84    28.8  690.76    38.4  689.93
    86.4  687.84    96.2  686.81     106  684.74   111.5  683.82   115.9  683.08
   126.5  684.21   135.6  686.54   155.2  687.84   174.9  692.35   184.7  694.29
   194.4  698.03     204  703.31   213.6  707.92   232.8  715.79   242.4  720.03
     252  724.81   271.2   735.6   280.8  740.49   290.4  745.11     300  749.44
   309.6  752.96   319.2  755.11   328.8  756.29   338.4  757.19   357.7  758.49
#Mann= 3 , 0 , 0
       0     .06       0   111.5    .045       0   126.5     .06       0
Bank Sta=111.5,126.5
XS Rating Curve= 0 ,0
Exp/Cntr=0.3,0.1

Type RM Length L Ch R = 1 ,17057.6 ,311.9,310.4,309.1
XS GIS Cut Line= 3
      1837757.46      541082.398     1837667.182      541250.801
     1837617.703      541369.725
#Sta/Elev= 25
       0  711.91     9.6   707.5    38.2  694.15    47.8  690.78    57.3  689.31
    95.5  688.14   105.1  687.76   114.6  687.14   124.2  685.74   133.8  683.57
   143.3  683.09   150.8  684.05   152.9  684.32   162.4  686.05     172  687.09
   181.5   689.2   191.1  694.87   200.3  701.86   209.5  707.15   255.5  732.01
   273.9  741.78   283.1  745.98   301.5  752.58   310.7  756.35   319.9  760.32
#Mann= 3 , 0 , 0
       0      .1       0   133.8    .045       0   150.8      .1       0
Bank Sta=133.8,150.8
XS Rating Curve= 0 ,0
Exp/Cntr=0.3,0.1

Type RM Length L Ch R = 1 ,16747.2 ,216.3,226.9,237.3
XS GIS Cut Line= 5
     1837547.695      540866.187     1837495.612      540913.062
     1837321.133       541293.27     1837297.695      541485.978
     1837185.716      541715.145
#Sta/Elev= 30
       0  755.84    61.3  745.18    79.8  740.98    99.3  732.86   177.1  694.75
   196.5  684.29   204.5  682.09   206.3   681.6     216   681.9   219.5  682.72
   235.5  687.07   245.2  688.07     323  690.87   332.7  692.32   342.5  697.12
   361.9  708.69   371.7  713.47   391.1  720.15   410.6  725.18     469  734.46
   546.6  752.18   604.9  763.77   682.5  781.53   741.4  786.82   770.8  792.68
   829.7  800.95   859.1  807.94     918  819.19   927.8  823.38   937.6  828.54
#Mann= 3 , 0 , 0
       0      .1       0   204.5    .045       0   219.5      .1       0
Bank Sta=204.5,219.5
XS Rating Curve= 0 ,0
Exp/Cntr=0.3,0.1

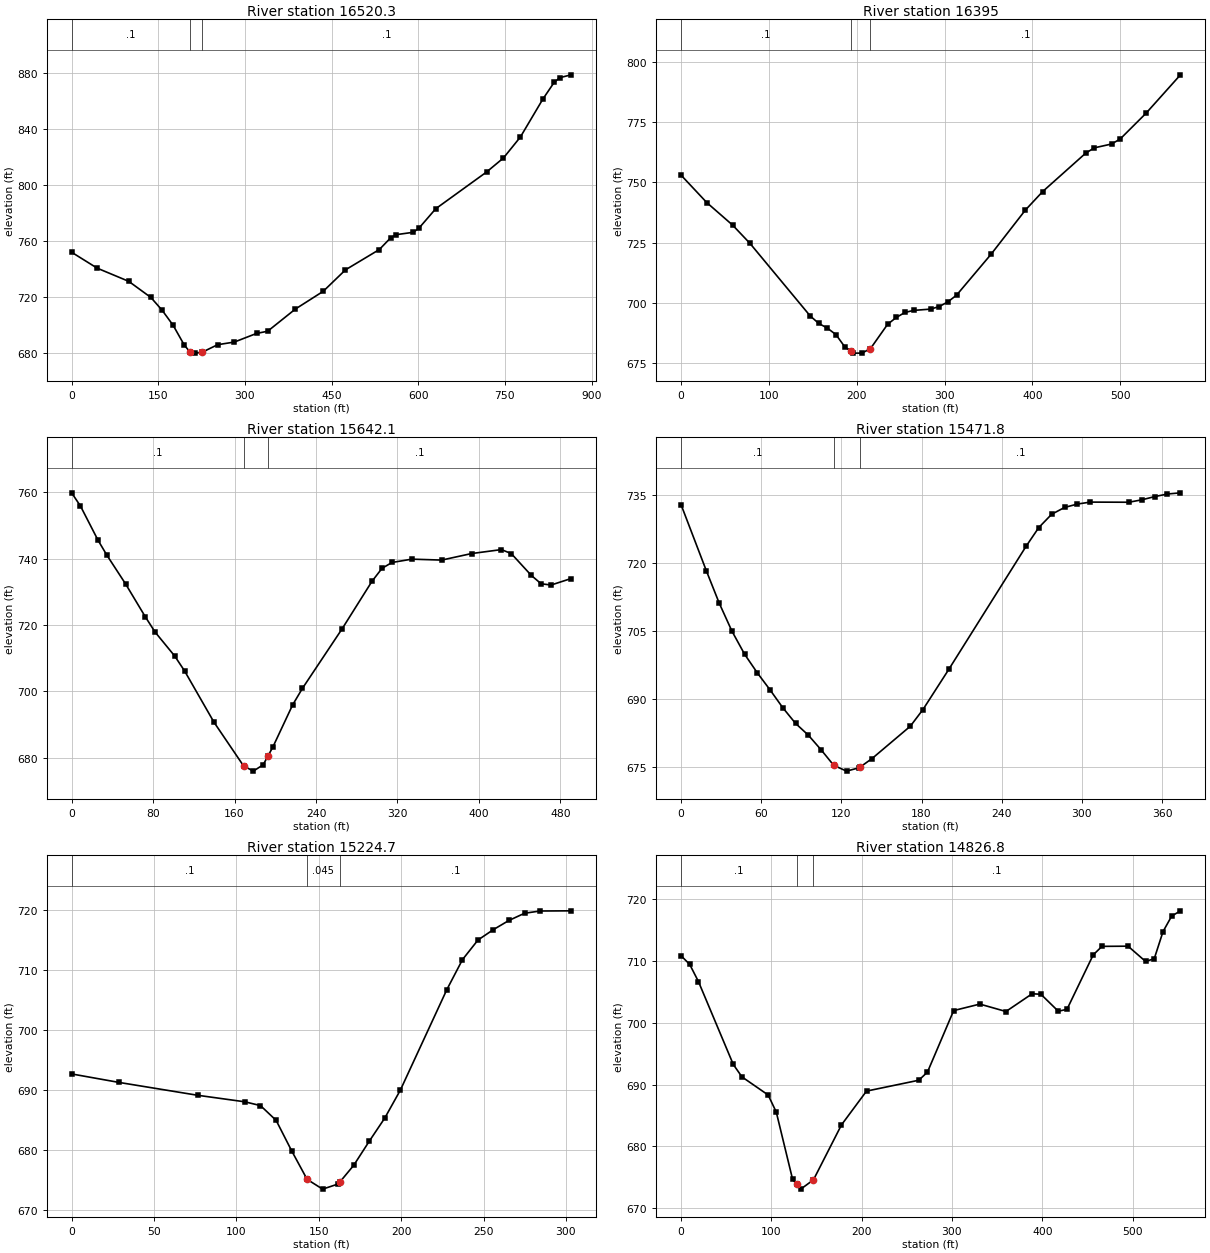
Type RM Length L Ch R = 1 ,16520.3 ,124.8,125.2,125.7
XS GIS Cut Line= 4
      1837407.07      540832.333     1837339.362      540873.999
      1837032.07      541121.395     1836748.216      541389.624
#Sta/Elev= 30
       0   751.8    44.2  740.44    98.8  731.03   137.2  719.48   156.5  710.44
   175.7   699.6     195  685.46   204.6  680.67   214.2  679.72   225.9  680.36
   252.7  685.74   281.6  687.63     320  693.78   339.3  695.37   387.4  711.25
   435.5   723.9     474  739.23   532.6  753.75   552.1  762.07   561.9  764.38
   591.2  766.06   600.9  768.89   630.2  782.89   718.1  809.11   747.4  819.15
   776.7  834.12   815.7  861.28   835.2  873.19     845  876.56   864.5  878.59
#Mann= 3 , 0 , 0
       0      .1       0   204.6    .045       0   225.9      .1       0
Bank Sta=204.6,225.9
XS Rating Curve= 0 ,0
Exp/Cntr=0.3,0.1

Type RM Length L Ch R = 1 ,16395   ,748.9,752.9,756.9
XS GIS Cut Line= 2
     1837279.841      540787.458     1836827.367      541131.425
#Sta/Elev= 30
       0  753.03    29.4  741.58    58.8  732.21    78.4  724.67     147  694.48
   156.8  691.34   166.6  689.39   176.4  686.68   186.2   681.7   193.2  679.77
     196     679   205.8     679   215.6  680.86   235.2  691.02     245  693.82
   254.8   695.9   264.6  696.76   284.2  697.31     294  698.38   303.8  700.34
   313.6  703.11   352.8  720.08     392  738.52   411.6  746.18   460.6  762.16
   470.4  764.36     490  765.95   499.8  768.03   529.2  778.73   568.4  794.72
#Mann= 3 , 0 , 0
       0      .1       0   193.2    .045       0   215.6      .1       0
Bank Sta=193.2,215.6
XS Rating Curve= 0 ,0
Exp/Cntr=0.3,0.1

Type RM Length L Ch R = 1 ,15642.1 ,175.4,170.3,165.3
XS GIS Cut Line= 4
     1836943.008      540172.089     1836901.341      540184.242
     1836738.147      540267.576     1836622.795      540504.834
#Sta/Elev= 30
       0  759.84     8.7  755.84      26  745.51    34.7  741.01      53  732.39
    72.3  722.52      82  717.88   101.3  710.65   110.9   706.2   139.8  690.74
   168.8  677.61   178.4  676.01   188.1  677.92   192.6  680.45   197.7  683.32
     217  695.94   226.6  700.91   265.7  718.91     295   733.2   304.8  737.09
   314.6  738.86   334.1  739.86   363.4  739.58   392.8  741.55   422.1  742.74
   431.8  741.53   451.4  734.98   461.1  732.44   470.9  732.07   490.5  734.02
#Mann= 3 , 0 , 0
       0      .1       0   168.8    .045       0   192.6      .1       0
Bank Sta=168.8,192.6
XS Rating Curve= 0 ,0
Exp/Cntr=0.3,0.1

Type RM Length L Ch R = 1 ,15471.8 ,247.2,247.1,246.8
XS GIS Cut Line= 4
     1836780.275      540059.304      1836708.66      540085.346
     1836628.004      540152.403     1836548.142      540327.751
#Sta/Elev= 30
       0  732.83      19  718.23    28.6  711.14    38.1  704.99    47.6   699.9
    57.2  695.77    66.7  692.04    76.2  688.13    85.7   684.7    95.3   682.1
   104.8   678.9   114.3  675.47   123.9  674.19   133.4  674.94   134.2  675.11
     143  676.96   171.6  684.06   181.1  687.74   200.4  696.56   258.2  723.61
   267.8  727.77   277.4  730.68   287.1  732.19   296.7  732.93   306.3  733.36
   335.2  733.33   344.9  733.86   354.5  734.57   364.1  735.14   373.8   735.4
#Mann= 3 , 0 , 0
       0      .1       0   114.3    .045       0   134.2      .1       0
Bank Sta=114.3,134.2
XS Rating Curve= 0 ,0
Exp/Cntr=0.3,0.1

Type RM Length L Ch R = 1 ,15224.7 ,404.6,397.9,391.2
XS GIS Cut Line= 3
      1836602.73      539871.742      1836508.98      539937.714
     1836364.883      540059.242
#Sta/Elev= 23
       0  692.64    28.7  691.23    76.4  689.09   105.1     688   114.6  687.37
   124.1  684.91   133.5  679.85   142.9  675.09   152.3  673.46   161.8  674.32
   162.7  674.62   171.2  677.43   180.6  681.43     190  685.28   199.5  689.95
   227.7  706.68   237.2  711.68   246.6  714.94     256  716.68   265.4   718.2
   274.9   719.4   284.3  719.77   303.1   719.8
#Mann= 3 , 0 , 0
       0      .1       0   142.9    .045       0   162.7      .1       0
Bank Sta=142.9,162.7
XS Rating Curve= 0 ,0
Exp/Cntr=0.3,0.1

Type RM Length L Ch R = 1 ,14826.8 ,356,360,363.8
XS GIS Cut Line= 4
     1836265.925      539527.992     1836252.036      539623.478
     1836198.216      539706.812     1836002.036      540005.423
#Sta/Elev= 30
       0  710.85     9.6  709.45    19.3  706.67    57.9  693.25    67.5  691.24
    96.5  688.31   105.5  685.54   123.6  674.64   128.3  673.83   132.6  673.08
  146.68  674.59   177.7  683.48   205.4  688.94   263.3   690.7   272.9  692.02
   301.9  701.97   330.9  703.02   359.8  701.82   388.8  704.69   398.5  704.61
   417.8  701.86   427.4  702.18   456.4  710.98   466.1  712.36     495  712.39
   514.4  709.92     524  710.36   533.7  714.75   543.3  717.26     553  718.11
#Mann= 3 , 0 , 0
       0      .1       0   128.3    .045       0  146.68      .1       0
Bank Sta=128.3,146.68
XS Rating Curve= 0 ,0
Exp/Cntr=0.3,0.1

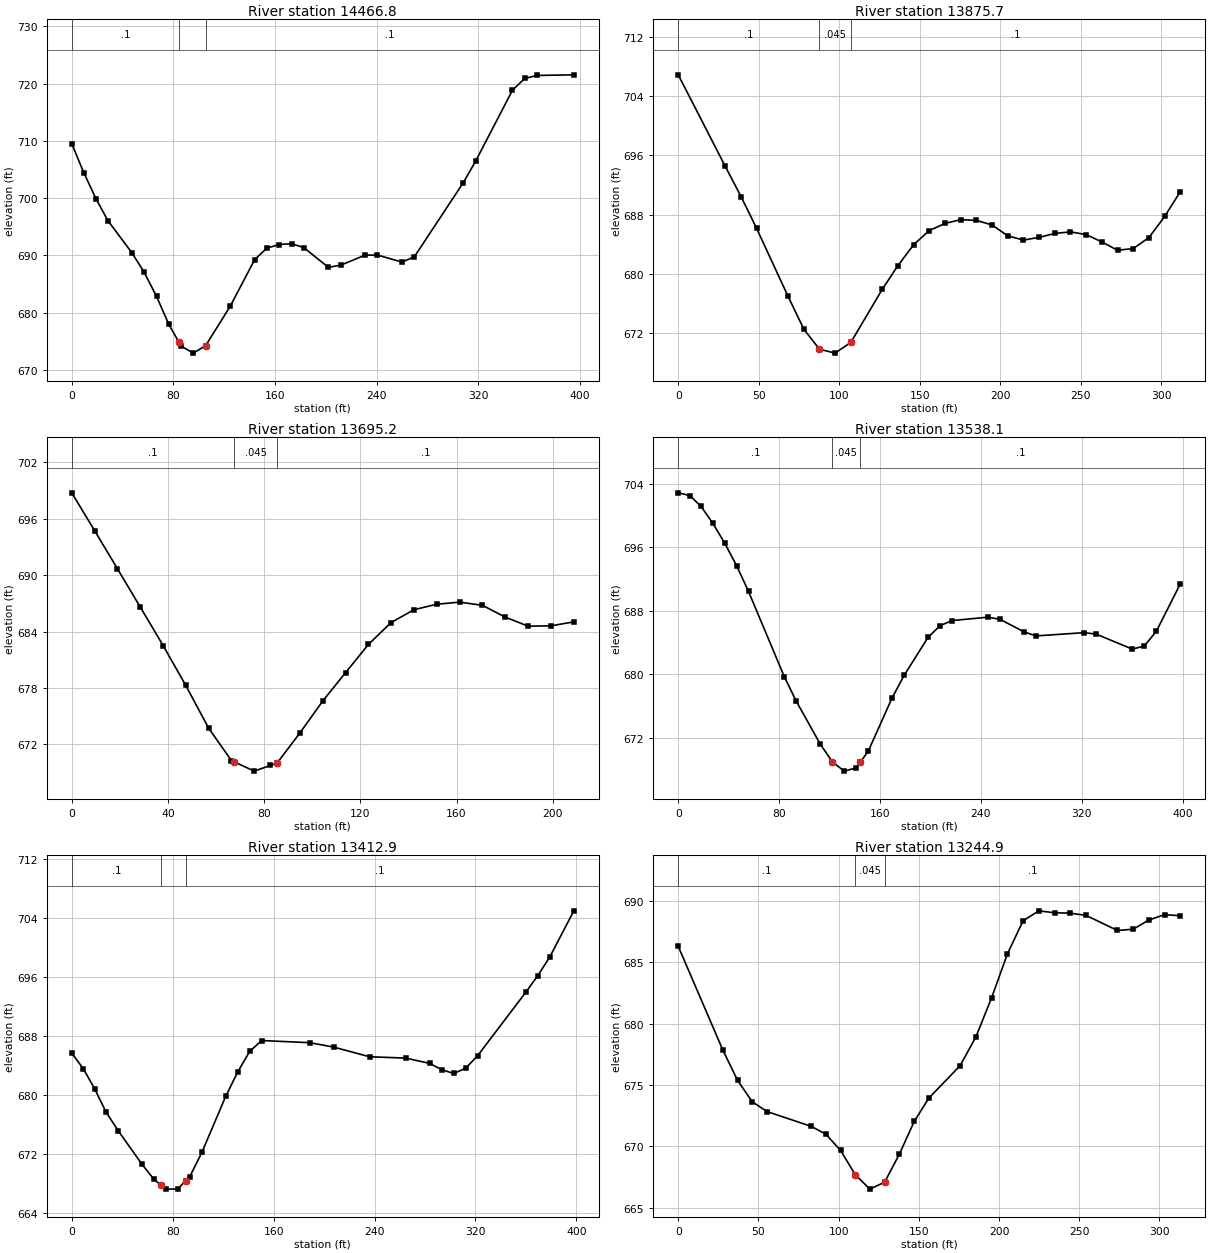
Type RM Length L Ch R = 1 ,14466.8 ,589.8,591.1,592.3
XS GIS Cut Line= 3
     1835967.313      539420.353     1835944.744       539462.02
     1835710.369      539718.964
#Sta/Elev= 30
       0  709.49     9.5  704.43      19  699.92    28.4  696.09    47.4  690.45
      57  687.06    66.7  682.87    76.4  677.98    84.2  674.91      86   674.2
    95.7  672.96   105.4  674.27   124.7  681.13     144  689.29   153.6  691.28
   163.3  691.91     173  692.05   182.6  691.38     202  687.93   211.6   688.3
   230.9  690.06   240.6  690.07   259.9  688.85   269.6  689.75   308.2  702.71
   317.9  706.46   346.9  718.84   356.5  720.88   366.2  721.41   395.2  721.52
#Mann= 3 , 0 , 0
       0      .1       0    84.2    .045       0   105.4      .1       0
Bank Sta=84.2,105.4
XS Rating Curve= 0 ,0
Exp/Cntr=0.3,0.1

Type RM Length L Ch R = 1 ,13875.7 ,180,180.5,180.7
XS GIS Cut Line= 2
     1835568.008      539007.159     1835345.786      539225.909
#Sta/Elev= 29
       0  706.88    29.2  694.53      39  690.46    48.7  686.15    68.2  676.99
      78  672.56    87.7  669.86    97.4  669.33   107.2  670.78   126.7  677.94
   136.4  681.13   146.2  683.96   155.9  685.87   165.7  686.83   175.4  687.34
   185.2  687.24   194.9  686.62   204.6  685.16   214.4  684.58   224.1  684.95
   233.9  685.48   243.6  685.69   253.4  685.32   263.1  684.33   272.8  683.21
   282.6  683.44   292.3  684.92   302.1  687.77   311.8  691.12
#Mann= 3 , 0 , 0
       0      .1       0    87.7    .045       0   107.2      .1       0
Bank Sta=87.7,107.2
XS Rating Curve= 0 ,0
Exp/Cntr=0.3,0.1

Type RM Length L Ch R = 1 ,13695.2 ,177,157.1,137.3
XS GIS Cut Line= 2
     1835423.911      538897.784     1835272.869      539041.881
#Sta/Elev= 25
       0  698.77     9.5  694.75      19  690.69    28.5  686.61      38  682.52
    47.4  678.28    56.9  673.74    66.4  670.28    67.5  670.15    75.9  669.16
    82.5  669.76    85.4  670.02    94.9  673.23   104.4  676.63   113.9  679.65
   123.4  682.65   132.8  684.97   142.3  686.33   151.8  686.92   161.3  687.14
   170.8   686.8   180.3  685.54   189.8  684.58   199.3  684.62   208.8  685.04
#Mann= 3 , 0 , 0
       0      .1       0    67.5    .045       0    85.4      .1       0
Bank Sta=67.5,85.4
XS Rating Curve= 0 ,0
Exp/Cntr=0.3,0.1

Type RM Length L Ch R = 1 ,13538.1 ,123.5,125.2,126.9
XS GIS Cut Line= 4
     1835274.605      538710.284     1835262.452      538734.589
     1835246.827      538923.826     1835234.675      539104.381
#Sta/Elev= 30
       0  702.83     9.1  702.49    18.1  701.12    27.2  699.05    36.7  696.54
    46.2  693.68    55.7  690.42    84.1  679.68    93.6  676.59   112.6   671.2
   122.1  668.98   131.6   667.8   141.1  668.21   144.4  668.94   150.6   670.3
   169.6  677.04   179.1  679.86   198.1  684.66   207.6  686.11     217  686.75
   245.6  687.18   255.2   686.9   274.2  685.32   283.7  684.82   321.8  685.23
   331.4  685.04   359.9  683.16   369.4  683.54     379   685.4     398  691.38
#Mann= 3 , 0 , 0
       0      .1       0   122.1    .045       0   144.4      .1       0
Bank Sta=122.1,144.4
XS Rating Curve= 0 ,0
Exp/Cntr=0.3,0.1

Type RM Length L Ch R = 1 ,13412.9 ,140.1,168,195.9
XS GIS Cut Line= 4
     1835179.119      538682.506     1835166.966      538706.812
     1835151.341      538896.048     1835139.188      539076.603
#Sta/Elev= 30
       0   685.7     9.1  683.61    18.1  680.89    27.2   677.7    36.7  675.21
    55.7  670.62    65.2  668.58      71  667.77    74.6  667.26    84.1  667.28
   90.35  668.42    93.6  668.97   103.1  672.23   122.1  679.87   131.6  683.17
   141.1  685.97   150.6  687.42   188.6  687.13   207.6  686.53   236.1  685.22
   264.7  685.04   283.7  684.32   293.2  683.47   302.8  682.95   312.3  683.67
   321.8  685.38   359.9  693.97   369.4  696.22     379  698.78     398  705.02
#Mann= 3 , 0 , 0
       0      .1       0      71    .045       0   90.35      .1       0
Bank Sta=71,90.35
XS Rating Curve= 0 ,0
Exp/Cntr=0.3,0.1

Type RM Length L Ch R = 1 ,13244.9 ,123.7,115.7,107.7
XS GIS Cut Line= 4
     1835182.591      538592.228     1835154.813      538592.228
     1835033.286      538633.895     1834934.327      538755.423
#Sta/Elev= 28
       0   686.3    27.8  677.85      37  675.38    46.1  673.64    55.3  672.84
    82.8  671.64      92     671   101.2  669.67   110.4  667.69   119.5  666.52
   128.7  667.09   137.9  669.38   147.1  672.03   156.2  673.93   175.8  676.59
   185.6  678.93   195.4  682.12   205.2  685.68     215  688.38   224.8  689.19
   234.6  689.03   244.4     689   254.2  688.82   273.8  687.59   283.6  687.69
   293.4  688.44   303.2  688.88     313  688.79
#Mann= 3 , 0 , 0
       0      .1       0   110.4    .045       0   128.7      .1       0
Bank Sta=110.4,128.7
XS Rating Curve= 0 ,0
Exp/Cntr=0.3,0.1

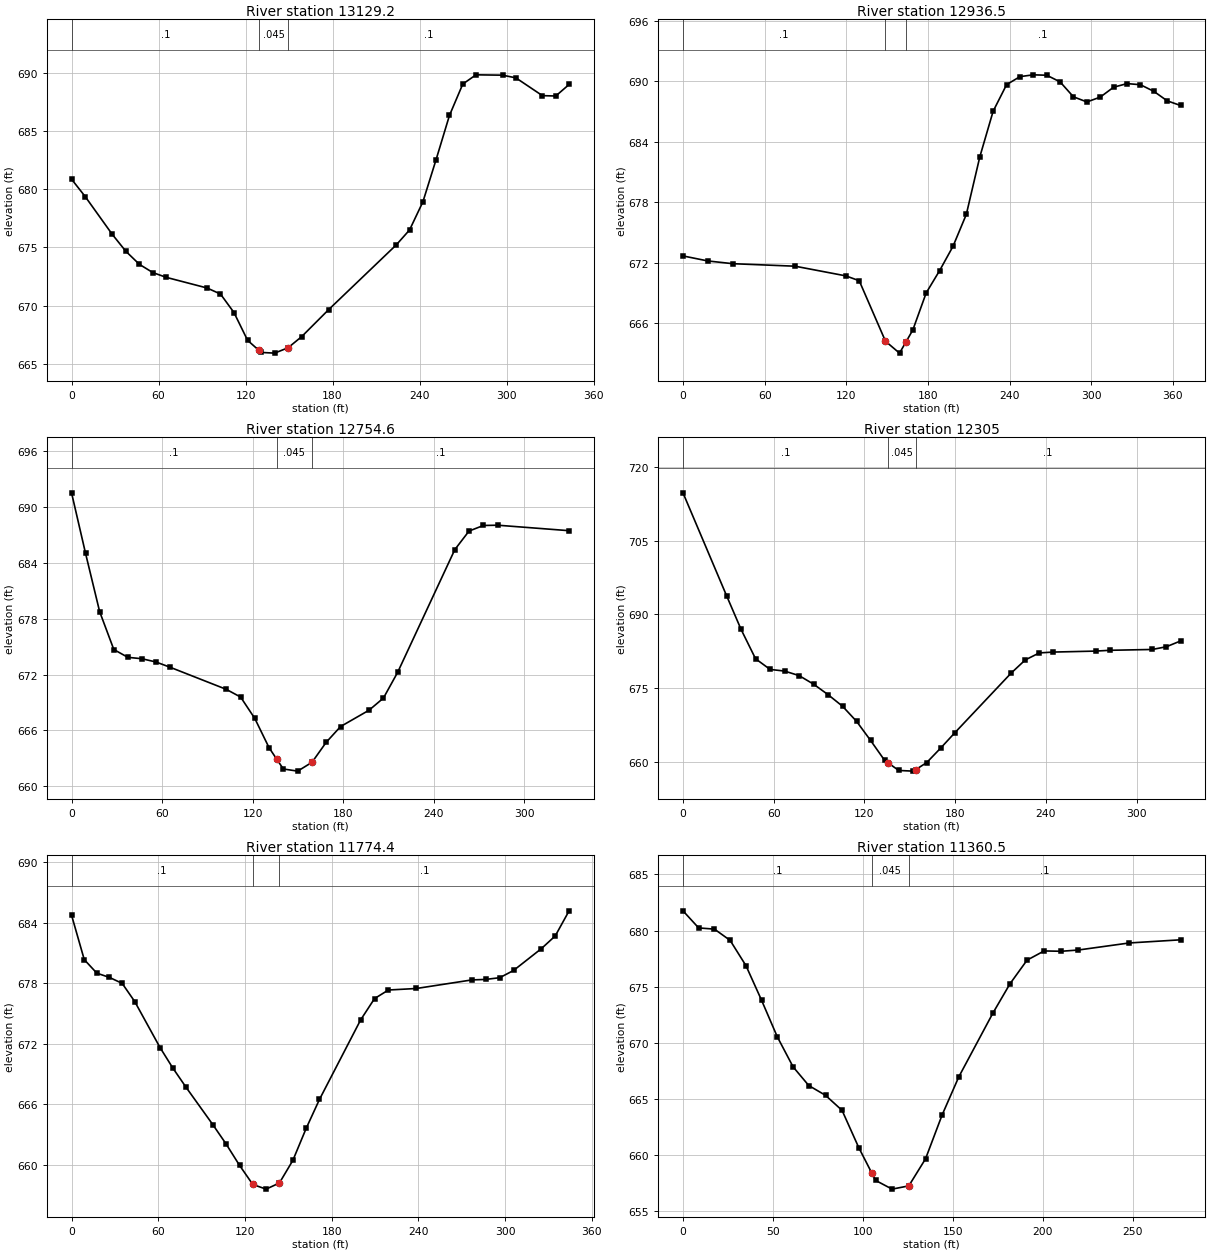
Type RM Length L Ch R = 1 ,13129.2 ,196.3,192.7,189.1
XS GIS Cut Line= 4
     1835127.036      538449.867     1835074.952      538470.701
     1834944.744      538576.603     1834863.147      538663.409
#Sta/Elev= 29
       0  680.87     9.4  679.38      28  676.14    37.4  674.68    46.8  673.55
    56.1  672.84    65.4  672.43    93.4  671.52   102.7     671     112  669.41
   121.4  667.02  129.27  666.15   130.7  665.98     140  665.92   149.3  666.38
   158.7  667.34   177.3  669.66   223.9  675.22   233.1  676.51   242.3  678.93
   251.4  682.56   260.6  686.35   269.8  689.05   278.9  689.84   297.2  689.81
   306.4  689.58   324.7  688.05   333.9  688.02   343.1  689.01
#Mann= 3 , 0 , 0
       0      .1       0  129.27    .045       0   149.3      .1       0
Bank Sta=129.27,149.3
XS Rating Curve= 0 ,0
Exp/Cntr=0.3,0.1

Type RM Length L Ch R = 1 ,12936.5 ,184.4,181.9,177.8
XS GIS Cut Line= 3
     1834958.633      538352.645     1834864.883      538409.937
     1834694.744      538600.909
#Sta/Elev= 30
       0  672.66    18.3  672.16    36.6  671.89    82.4  671.64   119.7  670.68
   129.5   670.2   148.8   664.2   159.1  663.02   163.8  664.12   168.9  665.32
   178.7  668.99   188.6  671.21   198.4  673.61   208.2  676.78   218.1  682.48
   227.9  687.01   237.8  689.65   247.6  690.44   257.4  690.62   267.3  690.58
   277.1  689.92   286.9  688.44   296.8  687.93   306.6  688.41   316.4  689.39
   326.3  689.75   336.1  689.64     346  688.98   355.8  688.04   365.6  687.58
#Mann= 3 , 0 , 0
       0      .1       0   148.8    .045       0   163.8      .1       0
Bank Sta=148.8,163.8
XS Rating Curve= 0 ,0
Exp/Cntr=0.3,0.1

Type RM Length L Ch R = 1 ,12754.6 ,445.9,449.6,454.6
XS GIS Cut Line= 3
     1834757.244       538180.77     1834738.147      538281.464
      1834602.73      538463.756
#Sta/Elev= 26
       0  691.54     9.3  685.02    18.6  678.78      28   674.7    37.3  673.86
    46.6  673.71    55.9  673.36    65.2   672.8   102.5  670.42     112  669.59
   121.4  667.29   130.9  664.13   135.9  662.92   140.3  661.86   149.8  661.63
   159.3  662.58   168.7  664.73   178.2  666.42   197.1  668.18   206.6  669.48
     216  672.24   253.9  685.44   263.3  687.43   272.8  688.03   282.3  688.06
   329.6  687.47
#Mann= 3 , 0 , 0
       0      .1       0   135.9    .045       0   159.3      .1       0
Bank Sta=135.9,159.3
XS Rating Curve= 0 ,0
Exp/Cntr=0.3,0.1

Type RM Length L Ch R = 1 ,12305   ,525.5,530.6,535.6
XS GIS Cut Line= 4
     1834449.952      537953.339     1834387.452      538038.409
     1834328.425      538097.437     1834232.938      538199.867
#Sta/Elev= 29
       0  714.72    28.8   693.8    38.4  686.93      48  680.94    57.6  678.77
    67.2  678.43    76.8  677.51    86.4  675.76      96  673.62   105.6  671.25
   114.8   668.2   124.1   664.3   133.4  660.24   135.5  659.78   142.7   658.2
   151.9  658.06  154.07  658.39   161.2   659.8   170.5  662.77   179.8  665.87
     217     678   226.4   680.7   235.7  682.13     245   682.3   273.1   682.5
   282.4  682.66   310.4  682.83   319.7  683.38   329.1  684.56
#Mann= 3 , 0 , 0
       0      .1       0   135.5    .045       0  154.07      .1       0
Bank Sta=135.5,154.07
XS Rating Curve= 0 ,0
Exp/Cntr=0.3,0.1

Type RM Length L Ch R = 1 ,11774.4 ,402.2,414,425.7
XS GIS Cut Line= 4
     1834090.577      537611.326     1834041.966      537661.673
     1833948.216      537720.701     1833807.591      537804.034
#Sta/Elev= 29
       0  684.76     8.8  680.35    17.5  679.01    26.2  678.59      35     678
    43.7   676.2    61.2  671.64      70  669.62    79.2   667.7    97.7     664
   106.9  662.08   116.2  659.96   125.4  658.06   134.6   657.6   143.8  658.21
   153.1  660.45   162.3  663.62   171.5  666.49     200  674.38   209.6  676.49
   219.2  677.34   238.5  677.49   276.9  678.34   286.5  678.39   296.2  678.56
   305.8  679.28     325  681.44   334.6   682.7   344.2  685.19
#Mann= 3 , 0 , 0
       0      .1       0   125.4    .045       0   143.8      .1       0
Bank Sta=125.4,143.8
XS Rating Curve= 0 ,0
Exp/Cntr=0.3,0.1

Type RM Length L Ch R = 1 ,11360.5 ,431.4,429.4,427.3
XS GIS Cut Line= 4
     1833904.813      537349.173     1833837.105      537331.812
     1833753.772      537335.284     1833639.188      537380.423
#Sta/Elev= 27
       0  681.76     8.7  680.24    17.5  680.13    26.2  679.13      35  676.88
    43.7  673.79    52.4  670.55    61.2  667.87    69.9  666.21    79.2  665.34
    88.4     664    97.7  660.68   104.8  658.46     107  657.77   116.2  656.99
   125.5  657.28   134.8  659.69     144  663.59   153.3  666.99   172.2  672.65
   181.7  675.26   191.2  677.37   200.7  678.19   210.1  678.16   219.6  678.27
     248   678.9   276.5  679.18
#Mann= 3 , 0 , 0
       0      .1       0   104.8    .045       0   125.5      .1       0
Bank Sta=104.8,125.5
XS Rating Curve= 0 ,0
Exp/Cntr=0.3,0.1

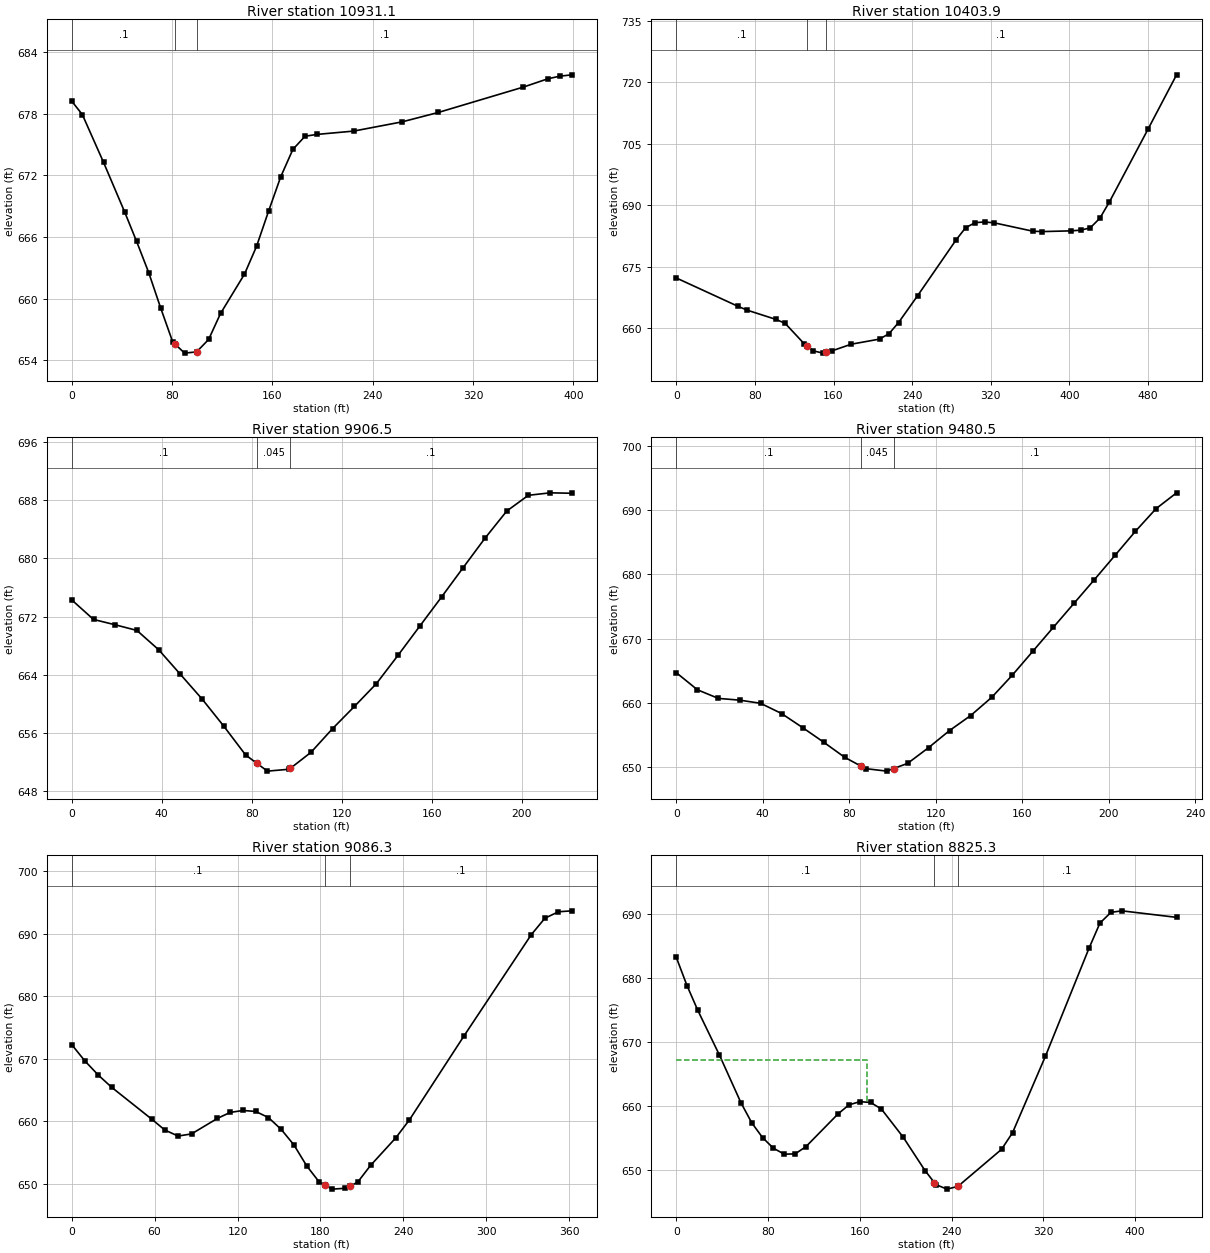
Type RM Length L Ch R = 1 ,10931.1 ,543,527.2,511.1
XS GIS Cut Line= 4
     1833953.425      536897.784     1833913.494      536911.673
     1833809.327      536925.562     1833587.105      537043.617
#Sta/Elev= 27
       0  679.24     8.5  677.93    25.4  673.28    42.3  668.43    51.8  665.57
    61.4  662.55    70.9  659.12    80.5  655.81    82.3   655.6      90   654.7
    99.6  654.82   109.2  656.03   118.7  658.56   137.8  662.39   147.4  665.09
     157  668.52   166.7  671.87   176.4  674.54   186.1  675.82   195.8     676
   224.8  676.32   263.5  677.22   292.5  678.14   360.3  680.61   379.6  681.41
   389.3  681.67     399   681.8
#Mann= 3 , 0 , 0
       0      .1       0    82.3    .045       0    99.6      .1       0
Bank Sta=82.3,99.6
XS Rating Curve= 0 ,0
Exp/Cntr=0.3,0.1

Type RM Length L Ch R = 1 ,10403.9 ,499,497.4,495.4
XS GIS Cut Line= 4
      1833633.98      536501.951     1833600.994      536566.187
     1833484.675      536666.881     1833243.355      536814.451
#Sta/Elev= 30
       0  672.21    63.2  665.23    72.2  664.33   101.1   662.1   110.7  661.13
   129.9  656.18   132.7  655.66   139.5  654.39   149.1  653.83  152.07  654.02
   158.8  654.42     178  656.01   206.8  657.26   216.4  658.58   226.1  661.29
   245.6   667.9   284.6  681.49   294.3  684.48   304.1  685.73   313.8  685.89
   323.6  685.67   362.6  683.64   372.4  683.54   401.6  683.72   411.4  683.89
   421.1  684.45   430.9  686.81   440.6  690.79   479.7   708.5   508.9  721.86
#Mann= 3 , 0 , 0
       0      .1       0   132.7    .045       0  152.07      .1       0
Bank Sta=132.7,152.07
XS Rating Curve= 0 ,0
Exp/Cntr=0.3,0.1

Type RM Length L Ch R = 1 ,9906.5  ,425.8,426,426.4
XS GIS Cut Line= 2
     1833279.813      536229.381     1833128.772      536392.576
#Sta/Elev= 26
       0   674.3     9.7  671.61    19.3  670.88      29   670.1    38.7  667.44
    48.3  664.08      58  660.67    67.7  656.92    77.3     653    82.2  651.88
      87  650.78    96.7  651.04    97.2  651.16   106.4  653.37     116  656.63
   125.7  659.67   135.4  662.78     145  666.66   154.7  670.68   164.4  674.69
     174  678.72   183.7  682.76   193.4   686.5     203  688.66   212.7     689
   222.4  688.94
#Mann= 3 , 0 , 0
       0      .1       0    82.2    .045       0    97.2      .1       0
Bank Sta=82.2,97.2
XS Rating Curve= 0 ,0
Exp/Cntr=0.3,0.1

Type RM Length L Ch R = 1 ,9480.5  ,399.9,394.2,388.1
XS GIS Cut Line= 4
     1832963.841      535975.909     1832927.383      535989.798
     1832854.466      536067.923       1832812.8      536142.576
#Sta/Elev= 27
       0  664.73     9.8  662.06    19.5  660.72    29.3  660.45      39  659.96
    48.7  658.37    58.4  656.19    68.2  653.91    77.9  651.56    85.5  650.18
    87.6   649.8    97.3  649.41   100.5  649.81     107  650.61   116.7  653.06
   126.4  655.72   136.2  658.06   145.9  660.88   155.4  664.32   164.9  668.04
   174.4  671.77   183.9  675.48   193.4  679.19   202.9  682.95   212.4  686.72
   221.9  690.22   231.4  692.69
#Mann= 3 , 0 , 0
       0      .1       0    85.5    .045       0   100.5      .1       0
Bank Sta=85.5,100.5
XS Rating Curve= 0 ,0
Exp/Cntr=0.3,0.1

Type RM Length L Ch R = 1 ,9086.3  ,260.8,260.9,261.1
XS GIS Cut Line= 4
     1832637.452      535689.451     1832583.633      535769.312
     1832517.661      535890.839     1832474.258      536010.631
#Sta/Elev= 30
       0  672.29     9.6  669.66    19.3   667.4    28.9  665.46    57.8  660.38
    67.4  658.62      77  657.66    86.7     658   105.5  660.49   114.7  661.44
     124  661.75   133.2  661.59   142.4  660.61   151.6  658.72   160.8  656.24
     170   652.9   179.3  650.25     183  649.82   188.5  649.17   197.7   649.3
  201.24  649.64   206.9  650.28   216.2  652.95   234.6   657.4   244.4  660.26
   283.6  673.59   332.6  689.89   342.4   692.5   352.2  693.53     362  693.68
#Mann= 3 , 0 , 0
       0      .1       0     183    .045       0  201.24      .1       0
Bank Sta=183,201.24
XS Rating Curve= 0 ,0
Exp/Cntr=0.3,0.1

Type RM Length L Ch R = 1 ,8825.3  ,552.3,556.6,560.9
XS GIS Cut Line= 3
      1832383.98      535562.714     1832311.063      535736.326
     1832191.272      535953.339
#Sta/Elev= 30
       0  683.26     9.4  678.82    18.8  674.96    37.7  667.96    56.5   660.5
    65.9  657.38    75.3  655.08    84.7  653.43    94.2   652.5   103.6  652.54
     113  653.66   141.2  658.81   150.6   660.2   160.1   660.7   169.5  660.57
   178.9  659.54   197.8  655.17   216.9  649.94     225  648.07   226.4  647.75
     236  647.04   245.5  647.46   283.6  653.25   293.2  655.85   321.8  667.76
   359.9  684.67   369.4  688.59     379  690.26   388.5   690.5   436.2  689.48
#Mann= 3 , 0 , 0
       0      .1       0     225    .045       0   245.5      .1       0
#XS Ineff= 2 , 0
          166.08  667.24
Permanent Ineff=
       F       F
Bank Sta=225,245.5
XS Rating Curve= 0 ,0
Exp/Cntr=0.3,0.1

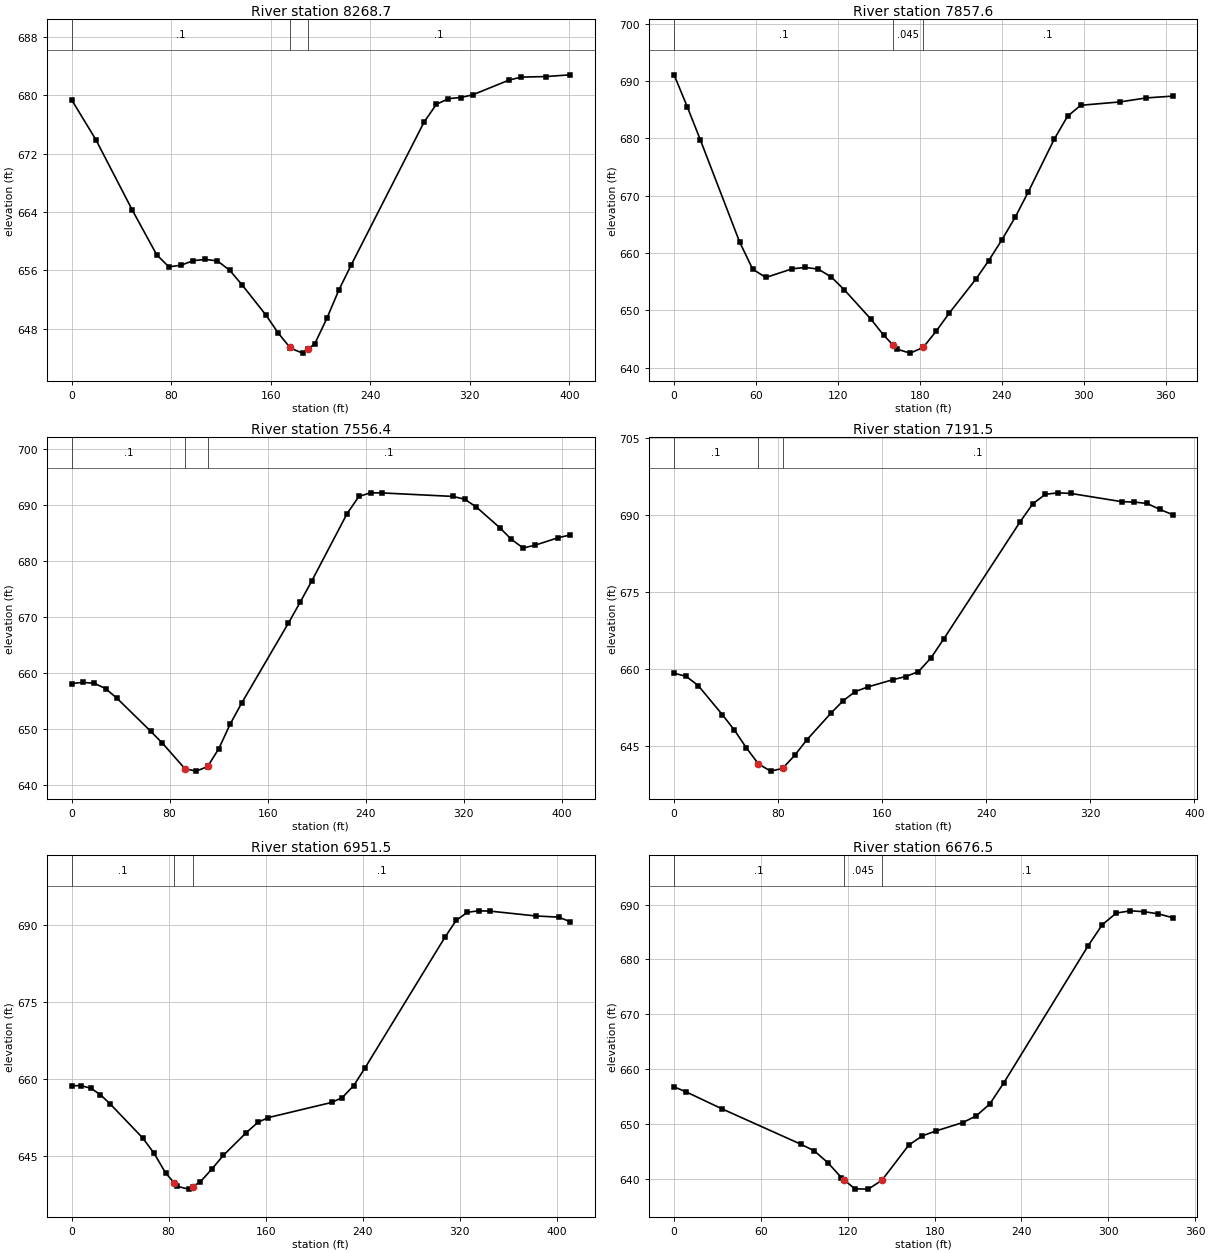
Type RM Length L Ch R = 1 ,8268.7  ,406.5,411.1,415.6
XS GIS Cut Line= 2
     1831901.341      535411.673     1831644.397      535718.964
#Sta/Elev= 30
       0  679.37    19.5   673.9    48.8  664.25    68.4  658.13    78.2  656.48
    87.9   656.7    97.7  657.32   107.5   657.5   117.2  657.29     127  656.02
   136.8  654.06   156.3  649.85   166.1  647.41   175.3  645.47   175.9  645.34
   185.6  644.66   190.3  645.26   195.4  645.92   205.2  649.44   214.9  653.34
   224.7  656.73   283.3  676.31   293.1  678.73   302.9  679.52   312.6  679.67
   322.4  680.04   351.7  682.07   361.5  682.47     381  682.54   400.6  682.78
#Mann= 3 , 0 , 0
       0      .1       0   175.3    .045       0   190.3      .1       0
Bank Sta=175.3,190.3
XS Rating Curve= 0 ,0
Exp/Cntr=0.3,0.1

Type RM Length L Ch R = 1 ,7857.6  ,299.6,301.3,302.9
XS GIS Cut Line= 3
     1831621.827      535140.839     1831548.911      535217.228
     1831345.786      535378.687
#Sta/Elev= 30
       0  691.11     9.6  685.57    19.2  679.78      48  661.93    57.6  657.17
    67.2  655.73    86.4  657.23      96  657.49   105.6  657.19   115.2   655.8
   124.8  653.55     144   648.5   153.6  645.63   160.7  643.86   163.3  643.21
   172.9  642.52   182.5  643.52   192.1  646.39   201.7  649.55   220.9  655.39
   230.5  658.68   240.2  662.33   249.8  666.22   259.4  670.64   278.6  679.94
   288.2  683.87   297.8  685.79   326.6  686.38   345.9  687.08   365.1  687.39
#Mann= 3 , 0 , 0
       0      .1       0   160.7    .045       0   182.5      .1       0
Bank Sta=160.7,182.5
XS Rating Curve= 0 ,0
Exp/Cntr=0.3,0.1

Type RM Length L Ch R = 1 ,7556.4  ,360.9,364.9,368.8
XS GIS Cut Line= 3
     1831404.813      534956.812      1831290.23      535034.937
     1831088.841       535212.02
#Sta/Elev= 30
       0  658.18     9.2  658.38    18.5  658.22    27.7  657.28      37  655.56
    64.7  649.63      74  647.57    92.5  642.98   101.7  642.55     111  643.36
   111.4   643.5   120.2  646.58   129.4  650.93   138.7  654.65     177  668.98
   186.6   672.7   196.2  676.55   224.9  688.51   234.5  691.56     244   692.2
   253.6  692.18   311.1  691.56   320.7  691.07   330.2  689.69   349.4  685.99
     359  683.89   368.5  682.36   378.1  682.85   397.3   684.2   406.8  684.67
#Mann= 3 , 0 , 0
       0      .1       0    92.5    .045       0   111.4      .1       0
Bank Sta=92.5,111.4
XS Rating Curve= 0 ,0
Exp/Cntr=0.3,0.1

Type RM Length L Ch R = 1 ,7191.5  ,248.4,240,231.7
XS GIS Cut Line= 3
     1831217.313      534663.409     1831090.577      534720.701
     1830903.077      534876.951
#Sta/Elev= 30
       0  659.21     9.3  658.59    18.5  656.81    37.1  651.14    46.4  648.12
    55.6  644.67    64.8  641.57    74.2  640.15    83.4  640.67    92.7  643.21
     102  646.22   120.5   651.4   129.8   653.8   139.1   655.6   148.8  656.52
   168.4  657.95   178.1  658.56   187.9  659.51   197.7  662.25   207.4   665.9
     266  688.65   275.8  692.17   285.5  694.02   295.3   694.3     305  694.18
   344.1  692.58   353.9   692.5   363.6  692.23   373.4  691.08   383.2  690.06
#Mann= 3 , 0 , 0
       0      .1       0    64.8    .045       0    83.4      .1       0
Bank Sta=64.8,83.4
XS Rating Curve= 0 ,0
Exp/Cntr=0.3,0.1

Type RM Length L Ch R = 1 ,6951.5  ,276,274.9,273.8
XS GIS Cut Line= 5
     1831064.536      534451.603     1831033.286      534475.909
     1830953.425      534557.506     1830911.758      534613.062
      1830781.55      534748.478
#Sta/Elev= 30
       0  658.64     7.9  658.63    15.8  658.16    23.8  656.88    31.7  655.12
    58.6  648.48    68.1  645.46    77.6  641.63    84.8  639.69    87.2  639.04
    96.7  638.51    99.8  638.98   106.2  639.94   115.7  642.42   125.2  645.09
   144.2  649.53   153.8  651.54   162.4  652.44   214.5  655.38   223.2  656.32
   232.6  658.63     242   662.1   307.8  687.48   317.1  690.79   326.5   692.4
   335.9  692.67   345.3  692.61   382.9  691.67   401.7  691.44   411.1  690.57
#Mann= 3 , 0 , 0
       0      .1       0    84.8    .045       0    99.8      .1       0
Bank Sta=84.8,99.8
XS Rating Curve= 0 ,0
Exp/Cntr=0.3,0.1

Type RM Length L Ch R = 1 ,6676.5  ,251.9,264,275.7
XS GIS Cut Line= 4
     1830826.688      534302.298     1830802.383      534335.284
     1830686.063      534468.964     1830620.091      534576.603
#Sta/Elev= 25
       0  656.78     8.2  655.89    32.8  652.82    87.6  646.34    96.9  645.13
   106.3  642.96   115.6  640.27   117.5  639.85   124.9  638.21   134.2  638.16
   143.6  639.77   162.2  646.19   171.5  647.86   180.9  648.75   199.5  650.29
   208.8   651.5   218.2  653.69   227.9  657.55   286.2  682.53   295.9  686.33
   305.6  688.45   315.3  688.85     325  688.69   334.7  688.29   344.4  687.61
#Mann= 3 , 0 , 0
       0      .1       0   117.5    .045       0   143.6      .1       0
Bank Sta=117.5,143.6
XS Rating Curve= 0 ,0
Exp/Cntr=0.3,0.1