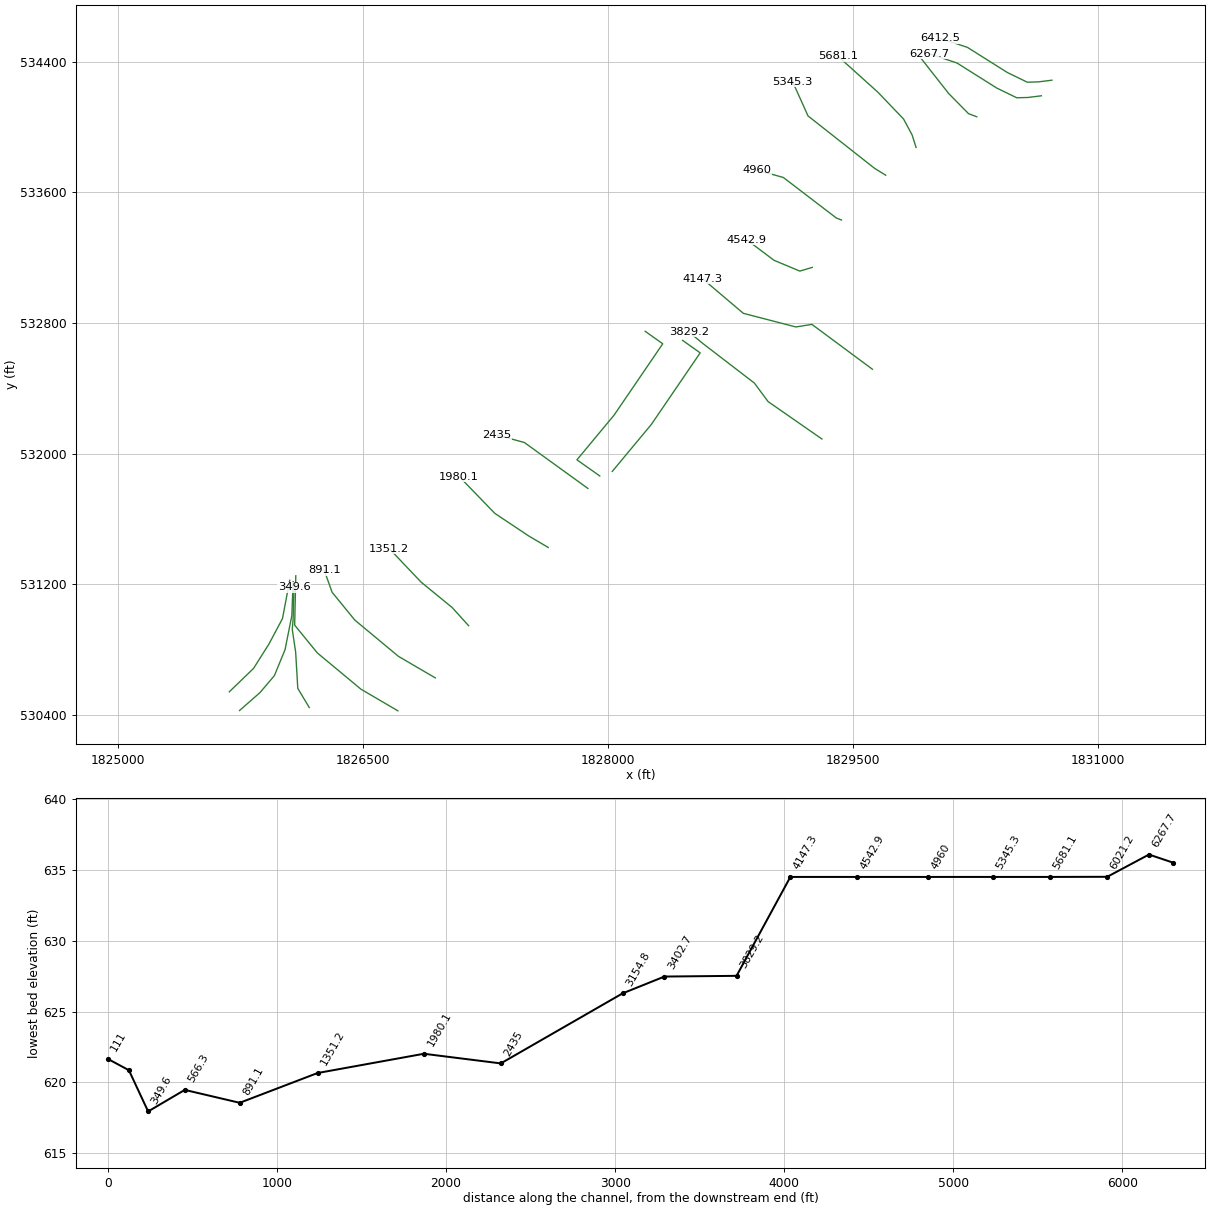
HEC-RAS study WILLSCK.prj: WILLSCK

--- WILLSCK.g01 (geometry) --- (continued)

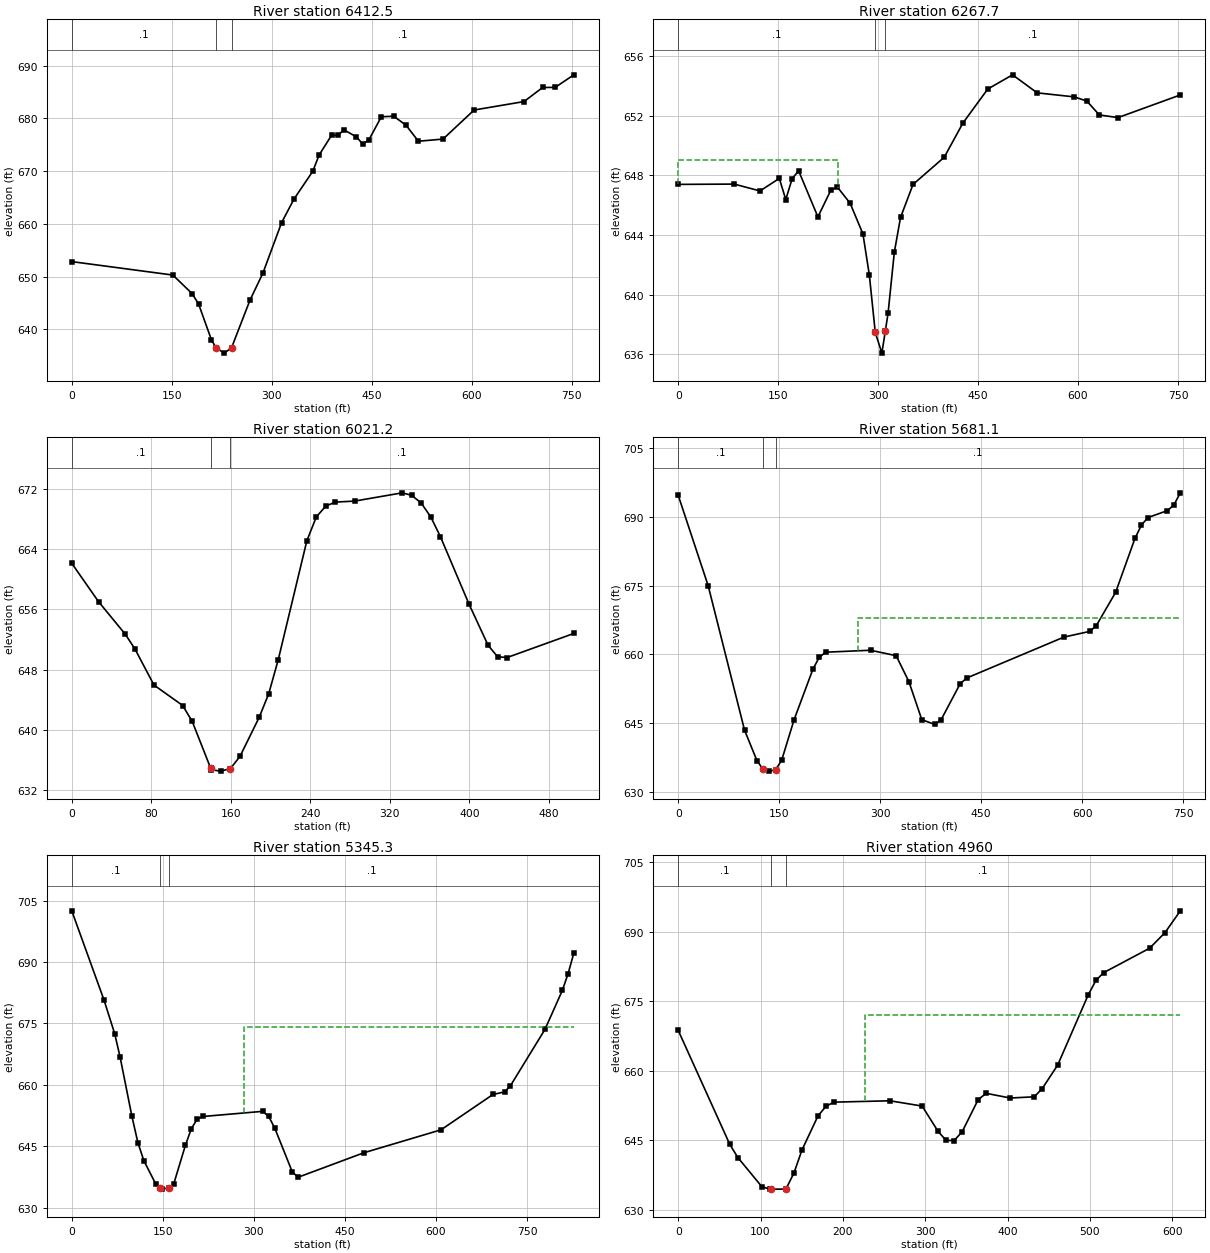
Type RM Length L Ch R = 1 ,6412.5  ,148.1,144.8,141.6
XS GIS Cut Line= 6
      1830719.05      534286.673     1830635.716      534276.256
     1830568.008       534274.52      1830446.48      534333.548
     1830201.979      534487.478     1830033.286      534543.617
#Sta/Elev= 30
       0  652.85   151.7   650.3   180.7  646.77   190.3  644.82   209.6  638.02
  216.64  636.47   228.9   635.5  239.77  636.51   267.5  645.56   286.8  650.65
   314.9  660.24   333.6  664.73   361.7  669.97   371.1  673.03   389.8  676.79
   399.2   676.8   408.6  677.82   427.3  676.49   436.7  675.12     446  675.96
   464.6  680.31   483.2  680.41   501.7   678.7   520.2  675.67   557.2  676.08
   603.8  681.59   678.7  683.19   706.7  685.86   725.5  685.88   753.5  688.26
#Mann= 3 , 0 , 0
       0      .1       0  216.64    .045       0  239.77      .1       0
Bank Sta=216.64,239.77
XS Rating Curve= 0 ,0
Exp/Cntr=0.3,0.1

Type RM Length L Ch R = 1 ,6267.7  ,253.7,246.5,239.4
XS GIS Cut Line= 6
     1830654.813      534191.187      1830571.48       534180.77
     1830503.772      534179.034     1830382.244      534238.062
     1830137.743      534391.992      1829969.05      534448.131
#Sta/Elev= 30
       0   647.4      84  647.42   122.7  646.96   151.7   647.8   161.4  646.38
     171  647.79   180.7  648.31   209.6  645.22   228.9     647   238.6  647.23
   257.9  646.14   277.2  644.08   286.8  641.32   295.7  637.47   305.6  636.08
   310.7  637.54   314.9  638.75   324.3  642.85   333.6  645.18   352.4   647.4
   399.2  649.22   427.3  651.52   464.6   653.8   501.7  654.75   538.7  653.54
   594.4  653.27   613.2  652.99   631.9  652.06     660  651.88   753.5   653.4
#Mann= 3 , 0 , 0
       0      .1       0   295.7    .045       0   310.7      .1       0
#XS Ineff= 2 , 0
           239.5  649.06
Permanent Ineff=
       F       F
Bank Sta=295.7,310.7
XS Rating Curve= 0 ,0
Exp/Cntr=0.3,0.1

Type RM Length L Ch R = 1 ,6021.2  ,346.9,340.1,333.4
XS GIS Cut Line= 4
      1830258.98      534062.714     1830208.633      534081.812
     1830087.105      534205.076      1829915.23      534423.826
#Sta/Elev= 30
       0  662.13    26.9  657.04    53.8  652.71    63.5  650.76    82.7  645.95
   111.6  643.23   121.2  641.11   139.6  634.94   140.4  634.68     150  634.51
   159.6  634.85   169.2  636.46   188.5  641.65   198.1  644.78   207.7  649.31
   236.5  665.13   246.1  668.32   255.7  669.75   265.3  670.27   284.5   670.4
   332.5   671.5   342.1  671.16   351.6  670.13   361.2  668.29   370.8  665.69
   399.6  656.72   418.8  651.24   428.4  649.71     438  649.61   505.1  652.81
#Mann= 3 , 0 , 0
       0      .1       0   139.6    .045       0   159.6      .1       0
Bank Sta=139.6,159.6
XS Rating Curve= 0 ,0
Exp/Cntr=0.3,0.1

Type RM Length L Ch R = 1 ,5681.1  ,326.4,335.8,345
XS GIS Cut Line= 5
     1829887.452      533875.214     1829863.147      533951.603
     1829811.063      534048.826     1829653.077      534213.756
     1829410.022      534432.506
#Sta/Elev= 30
       0  694.74    44.5  674.99    98.5  643.45   116.9   636.8   125.4  635.02
   135.3   634.5   144.5  634.77   153.7   636.9   172.1  645.74     200  656.75
   209.5  659.38     219  660.48   285.6  660.91   323.7  659.72   342.7  654.03
   361.8  645.74   380.8  644.72   390.3  645.68   418.8  653.59   428.5  654.84
   572.7  663.77   611.2  665.03   620.8  666.24   649.7  673.55   678.5  685.37
   688.1  688.27   697.8   689.9   726.6  691.41   736.2  692.64   745.8   695.3
#Mann= 3 , 0 , 0
       0      .1       0   125.4    .045       0   144.5      .1       0
#XS Ineff= 2 , 0
                          267.14          667.95
Permanent Ineff=
       F       F
Bank Sta=125.4,144.5
XS Rating Curve= 0 ,0
Exp/Cntr=0.3,0.1

Type RM Length L Ch R = 1 ,5345.3  ,385,385.4,385.7
XS GIS Cut Line= 4
     1829701.688      533705.076      1829633.98      533746.742
     1829225.994      534067.923     1829132.244      534276.256
#Sta/Elev= 30
       0  702.55      53  680.79    70.7  672.51    79.5  666.88    99.1  652.29
   108.9  645.89   118.7  641.48   138.3  635.77   145.5  634.84   148.1   634.5
   160.5   634.8   167.7  635.64   187.3  645.25   197.1  649.32   206.9  651.66
   216.7  652.27   314.6  653.52   324.4  652.27   334.2  649.51   363.6   638.6
   373.4  637.43   481.2  643.39   608.3     649   693.9  657.64     713  658.28
   722.5  659.72   779.6  673.55   808.2  683.08   817.7  687.17   827.2  692.23
#Mann= 3 , 0 , 0
       0      .1       0   145.5    .045       0   160.5      .1       0
#XS Ineff= 2 , 0
                          284.32          674.18
Permanent Ineff=
       F       F
Bank Sta=145.5,160.5
XS Rating Curve= 0 ,0
Exp/Cntr=0.3,0.1

Type RM Length L Ch R = 1 ,4960    ,411.2,417,422.8
XS GIS Cut Line= 4
     1829430.855       533430.77     1829399.605      533442.923
     1829074.952      533691.187     1828913.494      533736.326
#Sta/Elev= 30
       0  668.74    62.7  644.13    72.4  641.32   101.6  635.02   111.4   634.5
   112.5   634.5   130.8   634.5   140.6  637.99   150.3  642.94   169.8  650.31
   179.5  652.38   189.2  653.27   257.3  653.56   296.3  652.42   315.7  646.94
   325.5     645   335.2  644.99   344.9  646.88   364.4  653.83   374.1  655.17
   403.3  654.16   432.5  654.42   442.2  656.21   460.9  661.26   498.1  676.44
   507.4  679.54   516.7   681.2   572.6  686.48   591.2  689.82   609.9  694.55
#Mann= 3 , 0 , 0
       0      .1       0   112.5    .045       0   130.8      .1       0
#XS Ineff= 2 , 0
                          226.93          672.05
Permanent Ineff=
       F       F
Bank Sta=112.5,130.8
XS Rating Curve= 0 ,0
Exp/Cntr=0.3,0.1

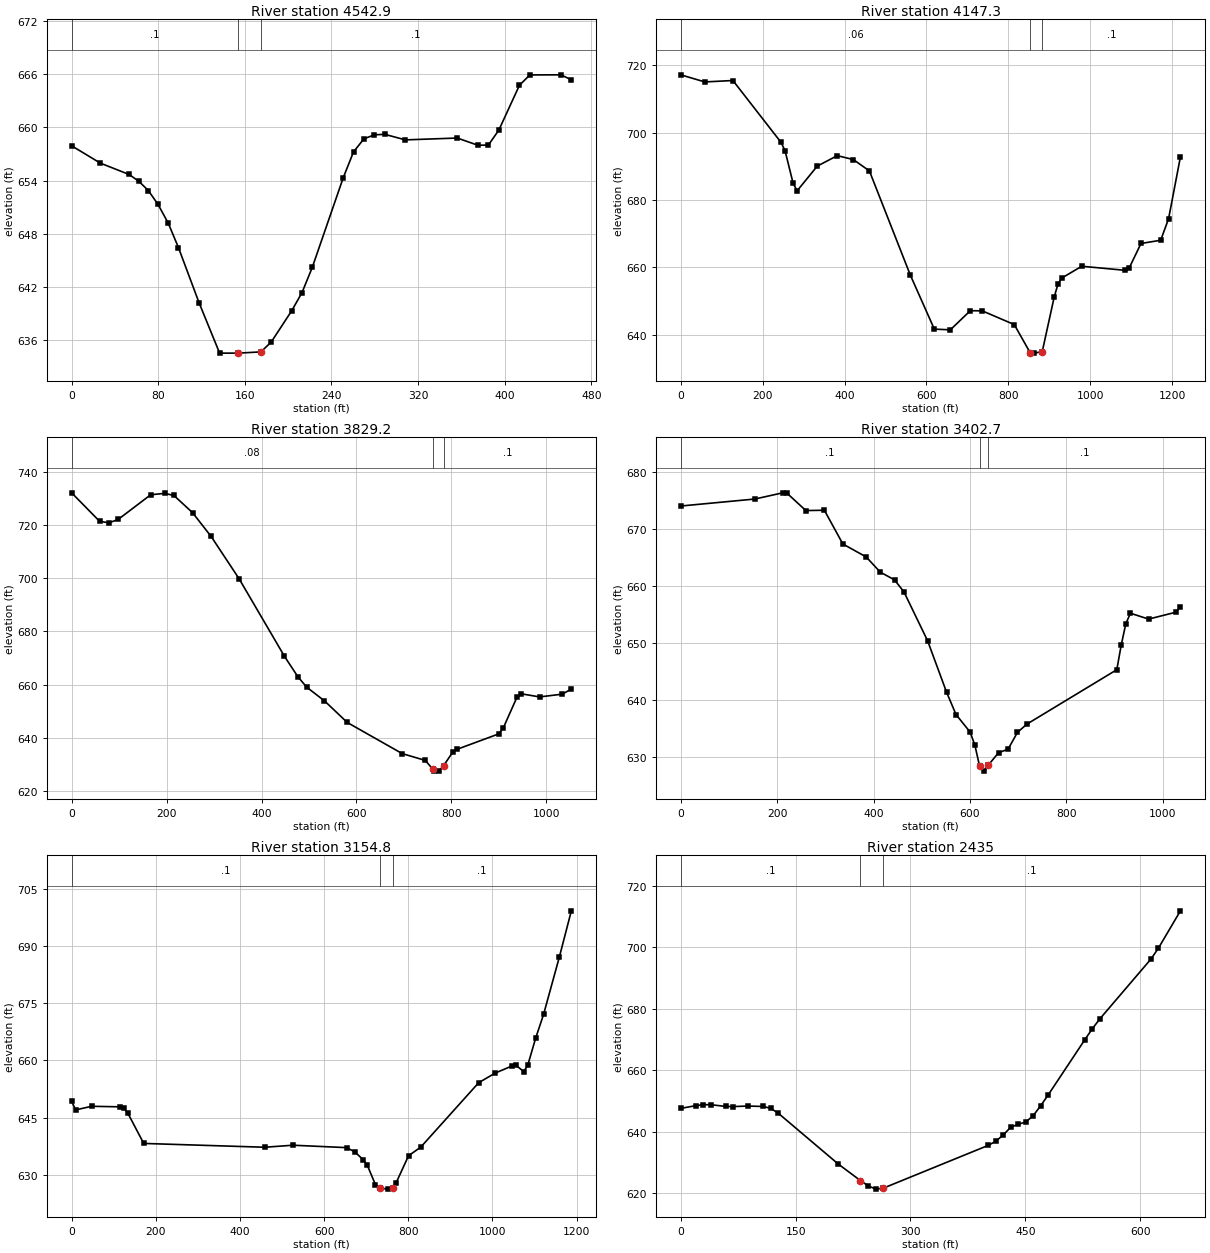
Type RM Length L Ch R = 1 ,4542.9  ,392.8,395.6,398.2
XS GIS Cut Line= 4
     1829252.036      533140.839     1829175.647       533118.27
     1829017.661      533184.242     1828849.258      533310.978
#Sta/Elev= 30
       0  657.92    26.6  655.96    53.1  654.68      62  653.92    70.8  652.87
    79.6  651.34    89.2  649.19    98.7  646.41   117.7  640.19   136.7   634.5
   154.1   634.5   174.8  634.64   184.3  635.74   203.3  639.29   212.8  641.34
   222.3  644.19   250.9  654.32   260.4  657.24     270  658.71   279.6  659.16
   289.2  659.22   308.3  658.59   356.2   658.8   375.4  657.98     385  658.01
   394.6  659.69   413.7  664.77   423.3  665.93     452  665.94   461.6  665.38
#Mann= 3 , 0 , 0
       0      .1       0   154.1    .045       0   174.8      .1       0
Bank Sta=154.1,174.8
XS Rating Curve= 0 ,0
Exp/Cntr=0.3,0.1

Type RM Length L Ch R = 1 ,4147.3  ,327.8,318.1,308.6
XS GIS Cut Line= 5
     1829620.091      532517.576     1829250.023      532791.889
     1829151.341      532776.256     1828830.161      532859.589
     1828580.161      533071.395
#Sta/Elev= 30
       0  717.14    58.8  715.03   127.4  715.45     245  697.06   254.8  694.54
   274.4  684.91   284.2   682.7   333.2  690.02   382.2  693.14   421.4  691.98
   460.6  688.61   560.6  657.65   619.1  641.63   658.2  641.42     707   647.1
   736.2  647.05   814.3  642.98   853.3  634.58   863.1   634.5   882.6  634.94
   911.6  651.04   921.3  655.14   930.9  656.84   979.1   660.3  1085.1  659.09
  1094.8  659.75  1123.7  667.06  1171.8  668.02  1191.1  674.42    1220   692.8
#Mann= 3 , 0 , 0
       0     .06       0   853.3    .045       0   882.6      .1       0
Bank Sta=853.3,882.6
XS Rating Curve= 0 ,0
Exp/Cntr=0.3,0.1

Type RM Length L Ch R = 1 ,3829.2  ,461.6,426.5,389.8
XS GIS Cut Line= 5
     1829311.063      532090.492     1828981.202      532319.659
     1828897.869      532432.506     1828583.633      532673.826
     1828495.091      532746.742
#Sta/Elev= 30
       0  732.08    58.8   721.4    78.4   720.8      98  722.08   166.5  731.35
   195.9  731.88   215.5  731.08   254.7  724.63   293.9  715.68   352.7  699.82
   448.4  670.65   476.5  663.02   495.2  659.06   532.6  653.93   580.6  645.81
   696.6  634.09   744.9  631.56  760.75   628.3   764.2  627.52   773.9  627.53
   783.5  629.55   802.8  634.62   812.5  635.75   899.5  641.49   909.2  643.66
   938.1  655.24   947.7  656.56   985.9   655.4  1033.7  656.44  1052.8  658.36
#Mann= 3 , 0 , 0
       0     .08       0  760.75    .045       0   783.5      .1       0
Bank Sta=760.75,783.5
XS Rating Curve= 0 ,0
Exp/Cntr=0.3,0.1

Type RM Length L Ch R = 1 ,3402.7  ,249.8,247.9,247.1
XS GIS Cut Line= 4
     1828027.614      531891.997     1828267.198      532180.191
     1828565.809      532617.691      1828458.17       532694.08
#Sta/Elev= 30
       0  674.08   153.8  675.31   211.4   676.4     221  676.29   259.5  673.28
   297.9  673.34   336.3   667.4   384.6  665.13     414  662.45   443.4   661.1
   463.1  658.97   512.1  650.38   551.3  641.37     571  637.42   600.4  634.32
   610.2     632     620   628.3   629.8  627.47   638.1  628.54   659.2  630.71
   678.9  631.32   698.5  634.29   718.1  635.74   904.5   645.3   913.9  649.73
   923.3  653.41   932.8  655.23   970.5   654.2    1027  655.41  1036.5  656.34
#Mann= 3 , 0 , 0
       0      .1       0     620    .045       0   638.1      .1       0
Bank Sta=620,638.1
XS Rating Curve= 0 ,0
Exp/Cntr=0.3,0.1

Type RM Length L Ch R = 1 ,3154.8  ,682.2,719.7,757.2
XS GIS Cut Line= 5
     1827951.225      531864.219     1827811.239      531962.939
     1828038.031      532235.747     1828336.642      532673.247
     1828229.003      532749.636
#Sta/Elev= 30
       0  649.29     9.5  647.03    47.6  647.98   114.2  647.84   123.7  647.45
   133.2  646.24   171.3  638.25   458.9  637.25   526.1  637.78   653.6  637.15
   673.2  636.03   692.8  633.99   702.6  632.57   722.2  627.42     732  626.55
   751.7  626.28   763.3  626.68   771.3  627.95   800.7  635.01   830.1  637.32
   967.5  654.16  1006.7  656.68  1045.9  658.51  1055.8  658.76  1074.6  657.06
    1084   658.7  1102.9  665.83  1121.8  672.08  1159.5   687.2  1187.7  699.18
#Mann= 3 , 0 , 0
       0      .1       0     732    .045       0   763.3      .1       0
Bank Sta=732,763.3
XS Rating Curve= 0 ,0
Exp/Cntr=0.3,0.1

Type RM Length L Ch R = 1 ,2435    ,454.1,454.9,455.7
XS GIS Cut Line= 3
     1827878.309       531787.83      1827489.42       532069.08
     1827322.753      532114.219
#Sta/Elev= 30
       0  647.62    19.6   648.5    29.4  648.82    39.2  648.82    58.8  648.25
    68.6  648.22    88.2  648.38   107.7  648.24   117.5  647.64   127.3  646.06
   205.7  629.51   234.6  624.14   244.9   622.4   254.7  621.34   264.4  621.64
   401.6  635.58   411.4  636.92   421.2  638.97     431   641.5   440.8  642.45
   450.6  643.19   460.3  645.23   470.1  648.49   479.9  652.01   527.9  670.03
   537.5  673.53   547.1  676.68   614.2  696.25   623.8  699.75   652.6  711.92
#Mann= 3 , 0 , 0
       0      .1       0   234.6    .045       0   264.4      .1       0
Bank Sta=234.6,264.4
XS Rating Curve= 0 ,0
Exp/Cntr=0.3,0.1

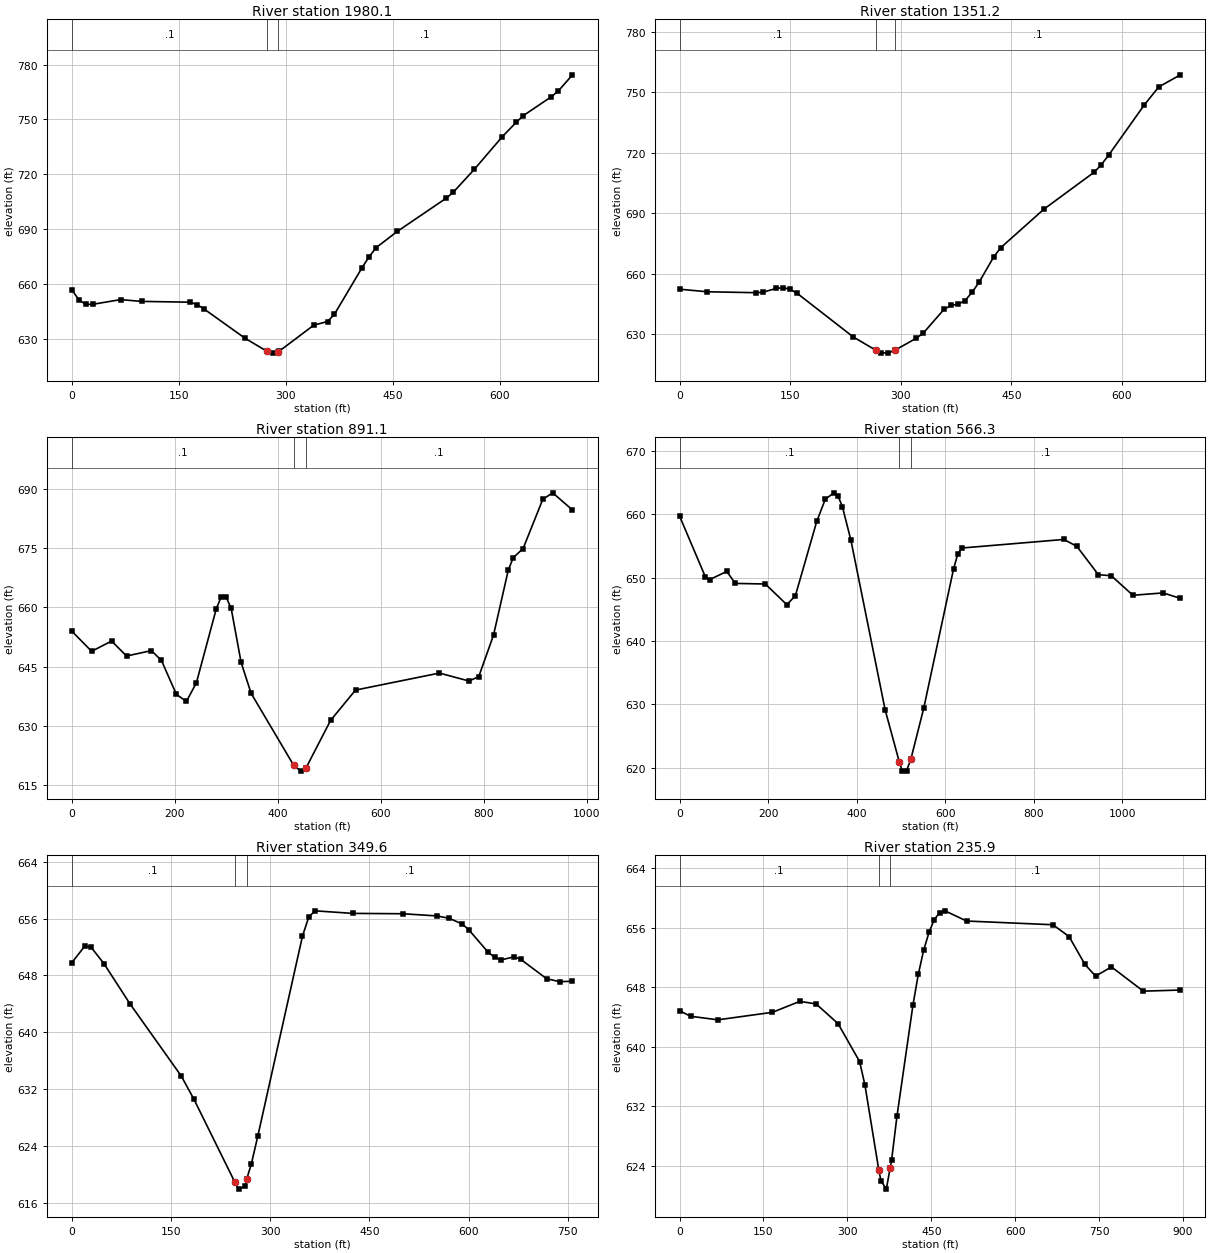
Type RM Length L Ch R = 1 ,1980.1  ,631,628.9,626.7
XS GIS Cut Line= 4
     1827635.253      531426.719     1827517.198      531496.164
     1827308.864      531635.052     1827090.114      531860.747
#Sta/Elev= 30
       0  656.79     9.8  651.34    19.6  648.71    29.4  648.76    68.5  651.33
    97.8  650.36   165.9  649.92   175.5  648.65   185.1   646.3   242.9  630.16
   273.4  623.07   281.4  622.02   288.4  622.85     291  623.16   339.2  637.34
   358.5  639.34   368.1   643.3     407  668.92   416.8  674.87   426.6  679.79
   456.1  688.66   524.9  706.92   534.7  710.16   564.2  722.72   603.4   740.6
   623.1  748.52   632.9  752.14   672.2  762.49     682  765.68   701.7  774.46
#Mann= 3 , 0 , 0
       0      .1       0   273.4    .045       0   288.4      .1       0
Bank Sta=273.4,288.4
XS Rating Curve= 0 ,0
Exp/Cntr=0.3,0.1

Type RM Length L Ch R = 1 ,1351.2  ,457.4,460.1,462.8
XS GIS Cut Line= 4
     1827148.274      530947.552      1827047.58      531058.664
     1826856.607      531214.914     1826662.163      531419.775
#Sta/Elev= 30
       0  652.33    37.5  651.06   103.1   650.6   112.5   650.8   131.2  652.74
   140.6  653.08     150  652.27   159.4   650.3   235.4  628.71   266.1   622.1
   273.3   620.9   282.8  620.66   292.3  622.14   320.8     628   330.3  630.48
   358.7  642.38   368.2  644.28   377.7  644.87   387.2  646.73   396.7  650.78
   406.4  655.92   425.9  668.25   435.7  672.94   494.1  691.98   562.3   710.3
     572  714.02   581.8  718.69   630.4  743.69   649.9  752.55   679.2  758.54
#Mann= 3 , 0 , 0
       0      .1       0   266.1    .045       0   292.3      .1       0
Bank Sta=266.1,292.3
XS Rating Curve= 0 ,0
Exp/Cntr=0.3,0.1

Type RM Length L Ch R = 1 ,891.1   ,327.3,324.9,321.8
XS GIS Cut Line= 5
     1826944.281      530628.108     1826718.587      530760.052
     1826451.225      530982.275     1826312.337      531152.414
     1826263.725       531287.83
#Sta/Elev= 30
       0  653.98    38.7  648.85    77.5  651.45   106.5  647.66   154.9  649.03
   174.3  646.53   203.3  637.96   222.7  636.18   242.1  640.86   280.8   659.6
   290.4  662.67   300.1  662.49   309.7  659.71     329  646.05   348.4  638.24
   431.2  620.01   444.9  618.56   454.6  619.24   502.9  631.41   551.2  639.05
   714.1  643.35   771.4  641.35   790.5  642.43   819.2  652.93   847.9  669.39
   857.5  672.52   876.7  674.84     915   687.3   934.2  688.92   972.6  684.58
#Mann= 3 , 0 , 0
       0      .1       0   431.2    .045       0   454.6      .1       0
Bank Sta=431.2,454.6
XS Rating Curve= 0 ,0
Exp/Cntr=0.3,0.1

Type RM Length L Ch R = 1 ,566.3   ,235.8,216.6,198.1
XS GIS Cut Line= 5
     1826715.114      530426.719      1826489.42      530558.664
     1826222.059      530780.886      1826083.17      530951.025
     1826090.114      531253.108
#Sta/Elev= 30
       0  659.72    58.1  650.15    67.8   649.7   106.5  650.99   125.9   649.1
   193.6  649.01   242.1  645.75   261.4  647.14   309.7  658.88     329  662.39
   348.4   663.4     358  662.88   367.7   661.2     387  655.88   464.2  629.13
   496.1  620.94   502.9  619.47   512.5  619.52   522.2  621.35   551.2  629.36
   618.6  651.36   628.2  653.73   637.7  654.69   867.7  656.04     897  654.96
   945.7  650.48   974.9  650.31  1023.7  647.23  1091.9   647.6  1130.9  646.74
#Mann= 3 , 0 , 0
       0      .1       0   496.1    .045       0   522.2      .1       0
Bank Sta=496.1,522.2
XS Rating Curve= 0 ,0
Exp/Cntr=0.3,0.1

Type RM Length L Ch R = 1 ,349.6   ,123.9,113.8,103.6
XS GIS Cut Line= 6
      1826172.58      530446.684     1826102.267      530563.872
     1826089.246      530785.226     1826068.413      530925.851
     1826073.621      530985.747      1826078.83      531181.927
#Sta/Elev= 30
       0  649.78    19.5  652.08    29.3  651.96    48.8  649.65    87.8  644.04
   165.6  633.85   184.9  630.56   246.1  619.02   252.4  617.95     262  618.36
   264.3  619.31   271.6  621.52   281.3  625.42   348.8  653.53   358.4  656.24
   367.9  657.08   424.7  656.72   500.6  656.67   552.1  656.36   570.5  656.03
   590.1  655.24   599.9  654.44   629.4  651.26   639.2  650.55     649  650.18
   668.6  650.61   678.4  650.28   717.7  647.54   737.3  647.12   756.9  647.18
#Mann= 3 , 0 , 0
       0      .1       0   246.1    .045       0   264.3      .1       0
Bank Sta=246.1,264.3
XS Rating Curve= 0 ,0
Exp/Cntr=0.3,0.1

Type RM Length L Ch R = 1 ,235.9   ,128.9,124.9,120.8
XS GIS Cut Line= 6
     1825745.496      530428.455     1825870.496       530537.83
     1825959.038      530641.997     1826024.142      530800.851
     1826065.809      531009.184     1826073.621      531217.518
#Sta/Elev= 30
       0  644.82    19.5  644.08    68.4   643.6   166.1  644.61   214.9  646.08
   244.2  645.73   283.3  643.09   321.9  637.99   331.4  634.84  356.07  623.47
     360     622   369.6  620.86   376.5   623.7   379.1  624.77   388.6  630.62
   417.3  645.61   426.8  649.71   436.3  652.92   445.9  655.34   455.4  657.06
     465  658.01   474.5  658.24   513.1  656.87   667.6  656.37   696.4  654.78
   724.8  651.04   743.8  649.47   772.2  650.71   829.1  647.45   895.4   647.6
#Mann= 3 , 0 , 0
       0      .1       0  356.07    .045       0   376.5      .1       0
Bank Sta=356.07,376.5
XS Rating Curve= 0 ,0
Exp/Cntr=0.3,0.1

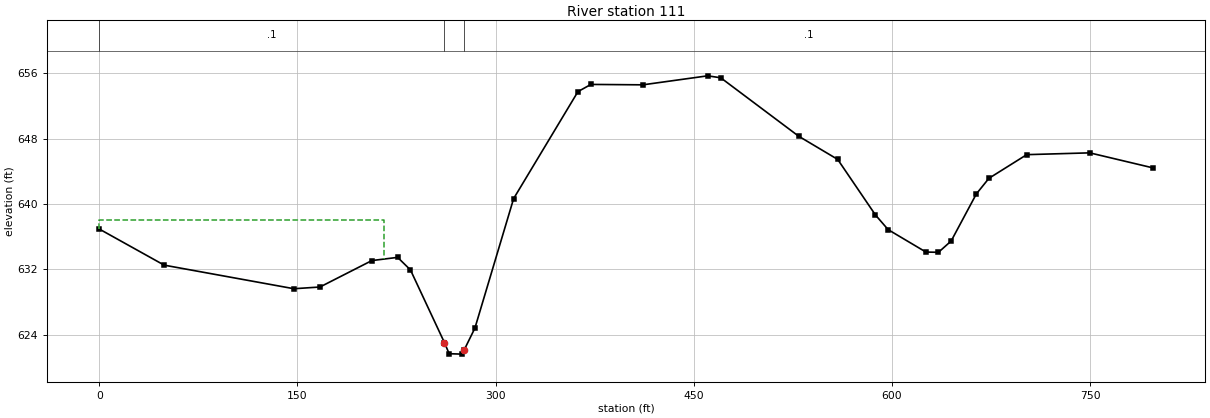
Type RM Length L Ch R = 1 ,111     ,102.4,111,119.6
XS GIS Cut Line= 5
     1825682.996      530543.039     1825831.434      530686.268
     1825925.184      530834.705     1826008.517      530990.955
     1826052.788       531225.33
#Sta/Elev= 30
       0  636.94    49.1  632.53   147.3  629.65     167  629.86   206.3  633.09
   225.8  633.48   235.5  631.95   261.2  623.08   264.8  621.71   274.6  621.66
   276.2  622.18   284.3  624.84   313.6  640.66   362.3  653.73   372.1  654.61
   411.4  654.56   460.5  655.66   470.4  655.42   529.4  648.28   558.9  645.45
   587.5  638.66   597.1  636.87   625.7  634.13   635.2   634.1   644.8  635.48
   663.9  641.24   673.4  643.14     702  646.03   749.7  646.25   797.4  644.42
#Mann= 3 , 0 , 0
       0      .1       0   261.2    .045       0   276.2      .1       0
#XS Ineff= 2 , 0
          215.41  638.06
Permanent Ineff=
       F       F
Bank Sta=261.2,276.2
XS Rating Curve= 0 ,0
Exp/Cntr=0.3,0.1

Chan Stop Cuts=-1
Use User Specified Reach Order=0
Composite Channel Slope=5